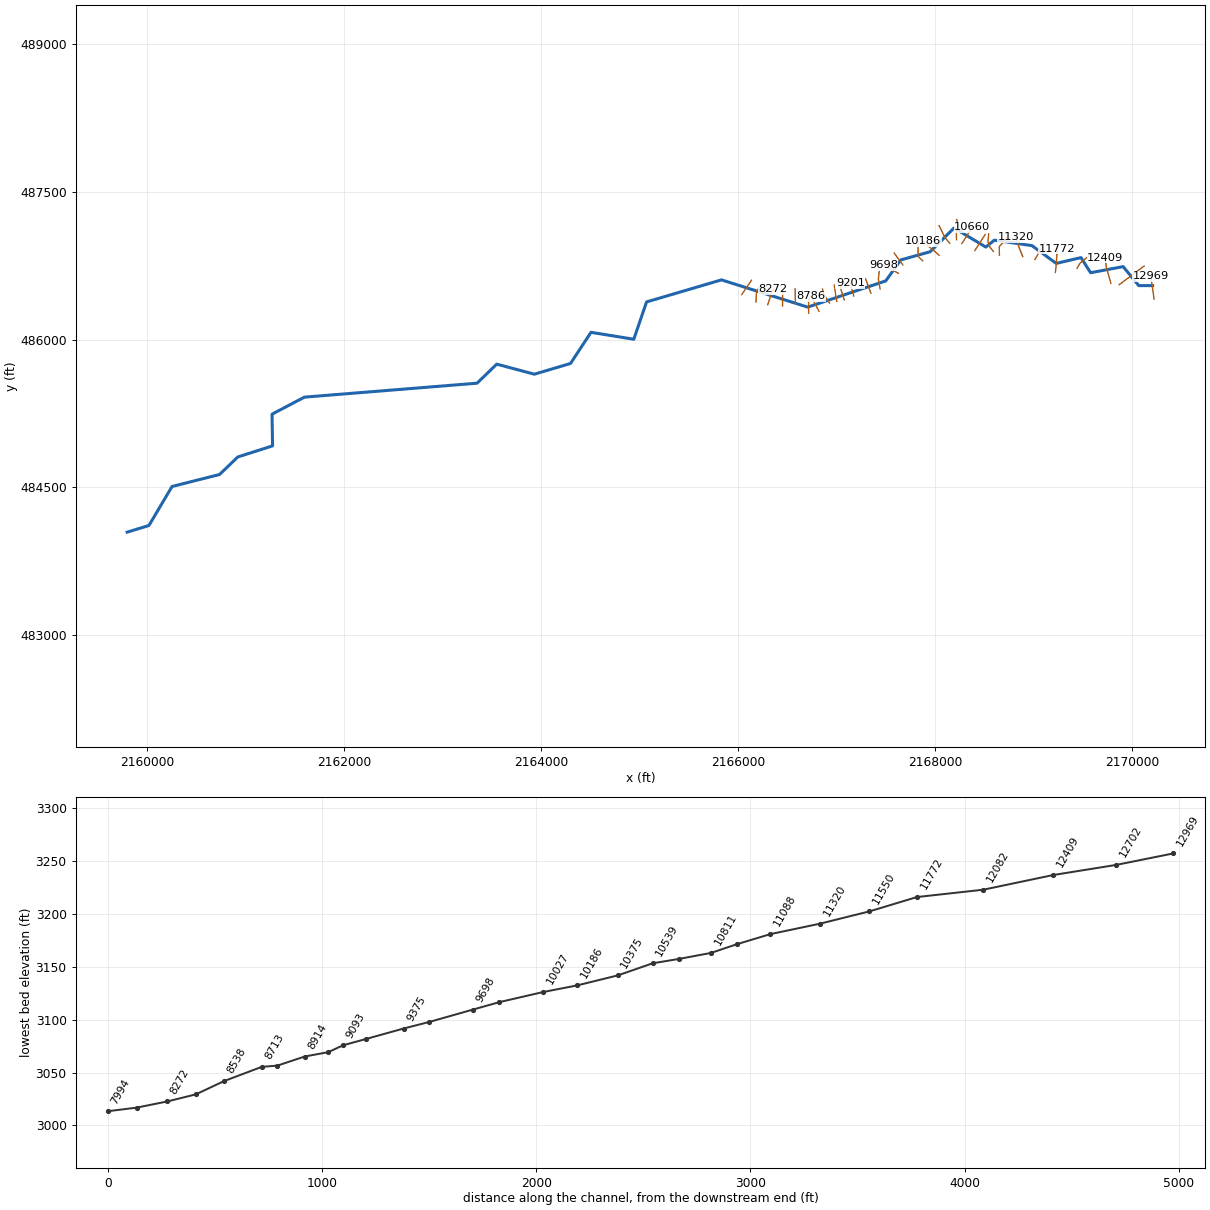
--- BEECHYRN.prj (project) ---

Proj Title=BEECHYRN
Current Plan=p01
Default Exp/Contr=0,0
English Units
Geom File=g01
Flow File=f01
Plan File=p01
Background Map Layer=Inundation Boundary (01pct Value_0)
BEGIN DESCRIPTION:
----------MODEL BY WOOD PLC 2021----------
Stream Name: Beechy Run
Flood Zone: Enhanced Approximate
Pocahontas County, WV
HEC-RAS Version: RAS 6.1
Vertical Datum: NAVD88
Projection: NAD 1983 StatePlane West Virginia S FIPS 4702 (US Feet)
Terrain: 1-meter LIDAR (FEMA Region III 3DEP collected 2016-2018)
Land Use: 2019 NLCD
Hydrologic Method:
WV SIR2010-5033 regression equations
Model Notes:
Normal depth tie in to Middle Fork Williams River
END DESCRIPTION:
DSS Export Rating Curves= 0
DSS Export Rating Curve Sorted= 0
DSS Export Volume Flow Curves= 0
DXF OffsetX= 0
DXF OffsetY= 0
DXF ScaleX= 0
DXF ScaleY= 0

--- BEECHYRN.p01 (plan) ---

Plan Title=Floodplain
Program Version=6.00
Short Identifier=Floodplain
Geom File=g01
Flow File=f01
Subcritical Flow
K Sum by GR= 0
Std Step Tol= 0.01
Critical Tol= 0.01
Num of Std Step Trials= 20
Max Error Tol= 0.3
Flow Tol Ratio= 0.001
Split Flow NTrial= 30
Split Flow Tol= 0.02
Split Flow Ratio= 0.02
Log Output Level= 0
Friction Slope Method= 1
Unsteady Friction Slope Method= 2
Unsteady Bridges Friction Slope Method= 1
Parabolic Critical Depth
Global Vel Dist= 0 , 0 , 0
Global Log Level= 0
CheckData=False
Encroach Param=-1 ,0,0, 0
Mapping Interval=1HOUR
Computation Time Step Use Courant=        0
Computation Time Step Use Time Series=    0
Computation Time Step Count To Double=0
Computation Time Step Max Doubling=0
Computation Time Step Max Halving=0
Computation Time Step Residence Courant=0
Run HTab= 0
Run UNet= 0
Run Sediment= 0
Run PostProcess= 0
Run WQNet= 0
Run RASMapper=-1
UNET Theta= 0
UNET Theta Warmup= 0
UNET ZTol= 0
UNET ZSATol= 0
UNET MxIter= 0
UNET Max Iter WO Improvement= 0
UNET MaxInSteps= 0
UNET DtIC= 0
UNET DtMin= 0
UNET MaxCRTS= 0
UNET WFStab= 0
UNET SFStab= 0
UNET WFX= 1
UNET SFX= 1
UNET Gravity=32.174
UNET 1D Methodology=Finite Difference
UNET DSS MLevel= 1
UNET Pardiso=0
UNET DZMax Abort= 0
UNET Use Existing IB Tables= 0
UNET Froude Reduction=False
UNET Froude Limit= 0
UNET Froude Power= 0
UNET D1 Cores= 0
UNET WindReference=Eulerian
UNET WindDragFormulation=Hsu (1988)
UNET D2 Coriolis=0
UNET D2 Cores= 0
UNET D2 Theta= 1
UNET D2 Theta Warmup= 1
UNET D2 Z Tol= 0.01
UNET D2 Volume Tol= 0.01
UNET D2 Max Iterations= 20
UNET D2 Equation= 0
UNET D2 RampUpFraction=0.1
UNET D2 TimeSlices= 1
UNET D2 Turbulence Formulation=Non-Conservative (original)
UNET D2 Eddy Viscosity=0.3
UNET D2 Transverse Eddy Viscosity=0.1
UNET D2 Smagorinsky Mixing=0
UNET D2 BCVolumeCheck=0
UNET D2 Cores=0
UNET D2 SolverType=PARDISO (Direct)
UNET D2 Minimum Iterations= 2147483647
UNET D2 Maximum Iterations= 2147483647
UNET D2 Restart Number= 10
UNET D2 Relaxation Coeff=1.3
UNET D2 SOR Precondition Iterations= 10
UNET D2 ILUT Maximum Fill= 8
UNET D2 ILUT Tolerance=1E-08
UNET D1D2 MaxIter= 0
UNET D1D2 ZTol=0.01
UNET D1D2 QTol=0.1
UNET D1D2 MinQTol=1
Write IC File= 0
Write IC File at Fixed DateTime=0
Write IC File at Sim End=0
Echo Input=False
Echo Parameters=False
Echo Output=False
Write Detailed= 0
HDF Write Warmup=0
HDF Write Time Slices=0
HDF Flush=0
HDF Compression= 1
HDF Chunk Size= 1
HDF Spatial Parts= 1
HDF Use Max Rows=0
HDF Fixed Rows= 1
Calibration Method= 0
Calibration Iterations= 20
Calibration Max Change=0.05
Calibration Tolerance=0.2
Calibration Maximum=1.5
Calibration Minimum=0.5
Calibration Optimization Method= 1
WQ AD Non Conservative
WQ ULTIMATE=-1
WQ Max Comp Step=1HOUR
WQ Output Interval=15MIN
WQ Output Selected Increments= 0
WQ Output face flow=0
WQ Output face velocity=0
WQ Output face area=0
WQ Output face dispersion=0
WQ Output cell volume=0
WQ Output cell surface area=0
WQ Output cell continuity=0
WQ Output cumulative cell continuity=0
WQ Output face conc=0
WQ Output face dconc_dx=0
WQ Output face courant=0
WQ Output face peclet=0
WQ Output face adv mass=0
WQ Output face disp mass=0
WQ Output cell mass=0
WQ Output cell source sink temp=0
WQ Output nsm pathways=0
WQ Output nsm derived pathways=0
WQ Create Restart=0
WQ Fixed Restart=0
WQ System Summary=0
WQ Write To DSS=0
Sorting and Armoring Iterations= 10
XS Update Threshold= 0.02
Bed Roughness Predictor= 0
Hydraulics Update Threshold= 0.02
Energy Slope Method= 1
Volume Change Method= 1
Sediment Retention Method= 0
Sediment TS Multiplier= 1
Warm Up Method= 0
XS Weighting Method= 0
Number of US Weighted Cross Sections= 1
Number of DS Weighted Cross Sections= 1
Upstream XS Weight=0
Main XS Weight=1
Downstream XS Weight=0
Number of DS XS's Weighted with US Boundary= 1
Upstream Boundary Weight= 1
Weight of XSs Associated with US Boundary= 0
Number of US XS's Weighted with DS Boundary= 1
Downstream Boundary Weight= 0.5
Weight of XSs Associated with DS Boundary= 0.5
Percentile Method= 0
Sediment Output Level= 3
Mass or Volume Output= 0
Output Increment Type= 1
Profile and TS Output Increment= 1
Transport Output Increment 1
XS Output Flag= 0
XS Output Increment= 10
Read HDF5 Sediment Hotstart= 0
Sediment Hotstart Type= 0
Write Gradation File= 0
Read Gradation Hotstart= 0
Write HDF5 File= 1
Write Binary Output= 1
Write DSS Sediment File= 0
DSS Sediment Output Type= 1
SV Curve= 0
Specific Gage Flag= 0
Subcell Erosion Methods= 0
Subcell Deposition Methods= 0
Advection Scheme= 1
Matrix Solver= 0
Implicit Weighting Factor= 1
Maximum Outer Loop Convergence Iterations= 5
Convergence Maximum Absolute= 0.001
Convergence RMSE= 0.0001
Grain Fractions Max Abs Error= 0.001
Max Subgrid Regions= 1
Max Subgrid Length Scale= 3.402823E+38
Initial Layer Thickness= 3.402823E+38
Min Layer Thickness= 3.402823E+38
Max Layer Thickness= 3.402823E+38
Number of Layers= 5

--- BEECHYRN.f01 (steady flow) ---

Flow Title=Flow
Program Version=6.10
Number of Profiles= 6
Profile Names=01pct,10pct,04pct,02pct,0_2pct,01plus
River Rch & RM=BEECHYRN,Main,12969
     736     393     520     624    1020    1090
River Rch & RM=BEECHYRN,Main,10027
     818     438     579     694    1130    1210
River Rch & RM=BEECHYRN,Main,8538
     912     491     647     775    1260    1350
River Rch & RM=BEECHYRN,Main,5012
    1040     561     737     882    1430    1530
Boundary for River Rch & Prof#=BEECHYRN,Main            , 1
Up Type= 0
Dn Type= 3
Dn Slope=0.10762
Boundary for River Rch & Prof#=BEECHYRN,Main            , 2
Up Type= 0
Dn Type= 3
Dn Slope=0.10762
Boundary for River Rch & Prof#=BEECHYRN,Main            , 3
Up Type= 0
Dn Type= 3
Dn Slope=0.10762
Boundary for River Rch & Prof#=BEECHYRN,Main            , 4
Up Type= 0
Dn Type= 3
Dn Slope=0.10762
Boundary for River Rch & Prof#=BEECHYRN,Main            , 5
Up Type= 0
Dn Type= 3
Dn Slope=0.10762
Boundary for River Rch & Prof#=BEECHYRN,Main            , 6
Up Type= 0
Dn Type= 3
Dn Slope=0.10762
DSS Import GetInterval= 0
DSS Import GetPeak= 0
DSS Import FillOption= 0

--- BEECHYRN.g01 (geometry) ---

Geom Title=Geometry
Program Version=6.10

River Reach=BEECHYRN        ,Main
Reach XY= 30
      2170208.22      486549.333     2170067.887      486549.125
     2169908.902      486742.298     2169578.681       486680.06
     2169481.117      486833.618     2169229.633      486774.862
     2168983.288      486955.506     2168601.157      487010.478
     2168514.839      486940.852     2168192.032      487134.969
     2167949.573       486893.31     2167651.467      486810.282
     2167498.649      486597.023     2166706.621      486330.737
     2165831.086      486607.474       2165070.4       486383.55
     2164940.596      486004.331     2164506.261      486074.779
2164298.31637677485758.433994142     2163931.014      485649.261
     2163549.229      485751.545     2163349.293      485557.937
     2161596.907      485416.198     2161267.646      485243.042
     2161273.155       484921.17     2160920.408      484808.576
     2160734.921       484630.41     2160252.563      484508.609
     2160017.906      484112.296     2159796.594      484044.404

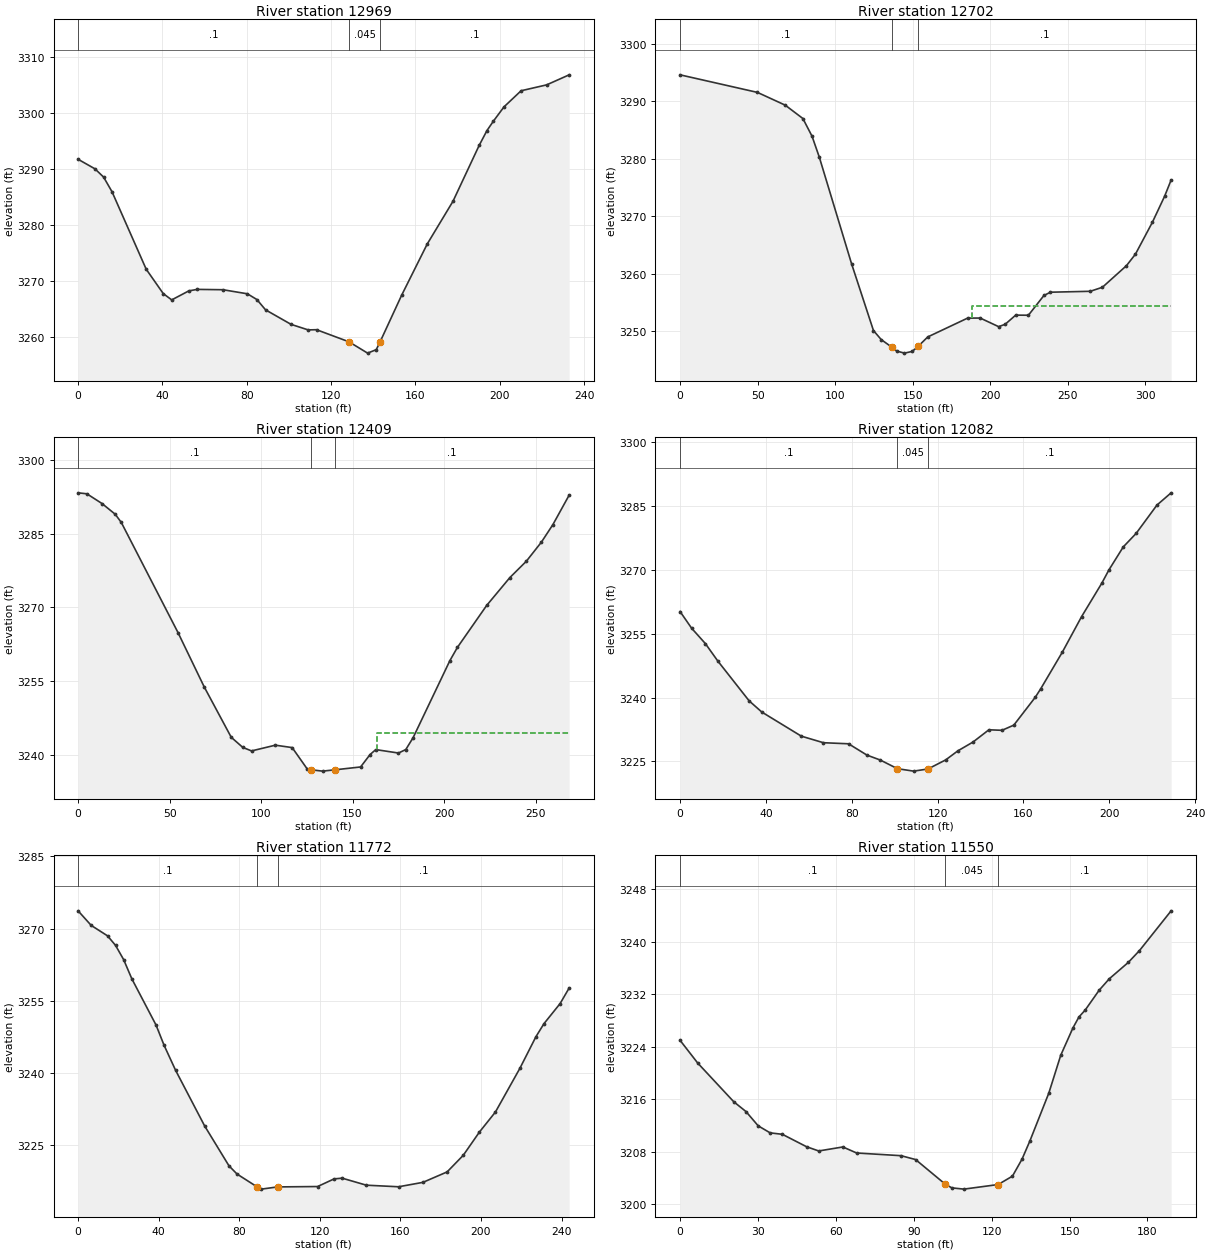
Type RM Length L Ch R = 1 ,12969   ,267.4,267.4,267.4
XS GIS Cut Line= 2
2170223.07816182 486413.211742292170190.13453843486643.817105978
#Sta/Elev= 30
       0 3291.73       8 3290.02    12.1 3288.54    16.1 3285.91    32.3 3272.05
    40.4 3267.68    44.4 3266.56    52.5 3268.17    56.5 3268.44    68.7 3268.38
    80.3 3267.65    84.8 3266.62    88.9 3264.78     101 3262.18   109.1 3261.19
   113.1 3261.22   128.5 3259.05   137.3 3257.03   141.4 3257.65  143.243259.062
   153.5 3267.44   165.6 3276.58   177.8 3284.22   190.2 3294.21   193.9 3296.87
     197 3298.58     202 3301.12   210.1    3304   222.2 3305.05   232.9 3306.85
#Mann= 3 ,-1,0
       0      .1       0   128.5    .045       0  143.24      .1       0
Bank Sta=128.5,143.24
XS Rating Curve= 0 ,0
Exp/Cntr(USF)=0,0
Exp/Cntr=0.3,0.1

Type RM Length L Ch R = 1 ,12702   ,273.9,293.4,315.3
XS GIS Cut Line= 2
2169868.21937872486558.2744188242170121.88527878486747.700253282
#Sta/Elev= 30
       0 3294.63    49.9 3291.57    67.8 3289.35    79.2 3287.02    85.1 3283.94
    89.8 3280.28   110.6 3261.71   124.7 3250.09   129.7 3248.52   136.4 3247.22
   139.7 3246.52   144.7 3246.16   149.7 3246.46   153.5 3247.34   159.7 3248.98
   185.4 3252.26   193.5 3252.27   205.4 3250.77   209.6 3251.18   216.4 3252.78
   224.6 3252.76   234.6  3256.2   238.8 3256.77   264.5 3256.93   272.3 3257.63
   287.8 3261.39   293.6  3263.4   304.5 3268.94   312.4 3273.48   316.6 3276.31
#Mann= 3 ,-1,0
       0      .1       0   136.4    .045       0   153.5      .1       0
#XS Ineff= 2 , 0
                          188.11         3254.34
Permanent Ineff=
       F       F
Bank Sta=136.4,153.5
XS Rating Curve= 0 ,0
Exp/Cntr(USF)=0,0
Exp/Cntr=0.3,0.1

Type RM Length L Ch R = 1 ,12409   ,342.3,326.9,297.6
XS GIS Cut Line= 3
2169784.68183674486572.6037472382169737.74309777486738.453958255
2169728.37014284486834.010176806
#Sta/Elev= 30
       0 3293.37     4.8 3293.17    13.1 3291.18    20.3    3289    23.6 3287.34
    54.6 3264.88    68.9 3253.82    83.7 3243.53      90 3241.47    94.8 3240.75
   107.8 3241.92     117 3241.43   125.3 3237.03   127.2 3236.91   133.6 3236.63
   140.2 3236.89   154.4 3237.48   159.6 3240.02   162.7 3241.02   175.1 3240.32
   179.1 3241.03   183.1 3243.45   203.2 3259.16   207.3 3261.85   223.3 3270.41
     236  3276.1     245 3279.43   253.2 3283.31   259.5 3286.89   268.4 3292.91
#Mann= 3 ,-1,0
       0      .1       0   127.2    .045       0   140.2      .1       0
#XS Ineff= 2 , 0
                          163.44         3244.44
Permanent Ineff=
       F       F
Bank Sta=127.2,140.2
XS Rating Curve= 0 ,0
Exp/Cntr(USF)=0,0
Exp/Cntr=0.3,0.1

Type RM Length L Ch R = 1 ,12082   ,296.2,309.9,315
XS GIS Cut Line= 3
2169440.66710645486724.5289832682169472.78713925486778.885961852
2169601.26727045486883.481966096
#Sta/Elev= 30
       0 3260.16     5.4 3256.24    11.8 3252.64    17.6 3248.55    32.2 3239.21
    38.1 3236.59    56.5 3230.94    66.8  3229.4    78.5 3229.15    87.1 3226.49
    93.3 3225.34   101.3 3223.31   108.8 3222.74   115.5 3223.24   123.8 3225.38
   129.4 3227.48   136.5 3229.56   143.9 3232.43     150 3232.31   155.5 3233.52
   165.5 3240.05   168.1 3242.09   178.1 3250.62   187.1 3258.97   196.5 3266.79
   199.8 3269.89   206.5  3275.3   212.5 3278.47   222.2 3285.11   228.8 3287.98
#Mann= 3 ,-1,0
       0      .1       0   101.3    .045       0   115.5      .1       0
Bank Sta=101.3,115.5
XS Rating Curve= 0 ,0
Exp/Cntr(USF)=0,0
Exp/Cntr=0.3,0.1

Type RM Length L Ch R = 1 ,11772   ,224.3,221.5,199.2
XS GIS Cut Line= 3
2169221.00801041486682.7138960652169229.03008252 486752.29288752
 2169240.6701888486925.694569999
#Sta/Elev= 30
       0 3273.69     6.5 3270.66    14.6 3268.49    18.6  3266.5    22.6 3263.55
    26.7 3259.53    38.7 3249.93    42.7 3245.71    48.4 3240.52    62.8 3228.96
    74.9 3220.65    78.9 3218.94    88.9 3216.26      91  3215.8      99 3216.26
   118.9 3216.34   127.1 3217.93   131.1 3218.08   143.1 3216.62   159.1 3216.29
   171.2 3217.21   183.2 3219.38   191.2 3222.83   199.2 3227.65   207.2 3231.85
   219.3 3240.91   227.3 3247.51   231.3 3250.23   239.3  3254.4   243.8 3257.65
#Mann= 3 ,-1,0
       0      .1       0    88.9    .045       0      99      .1       0
Bank Sta=88.9,99
XS Rating Curve= 0 ,0
Exp/Cntr(USF)=0,0
Exp/Cntr=0.3,0.1

Type RM Length L Ch R = 1 ,11550   ,214.5,230.1,246.6
XS GIS Cut Line= 2
2169013.25228458  486815.37862982169110.43597356486977.625974967
#Sta/Elev= 30
       0 3224.98     6.8 3221.51    20.7  3215.6    25.4 3214.11    30.1 3211.93
    34.7 3210.86    39.4 3210.64    48.7 3208.75    53.4  3208.1    62.7 3208.71
      68 3207.79    85.1 3207.38    90.7 3206.79   102.2 3203.01   104.7 3202.47
   109.3 3202.28   122.5 3202.98     128 3204.26   131.7 3206.86   134.7 3209.61
     142 3216.92   146.6  3222.7   151.3 3226.87   153.6 3228.53     156 3229.58
   161.4 3232.62   165.3 3234.36   172.6 3236.85   176.9 3238.65   189.1 3244.72
#Mann= 3 ,-1,0
       0      .1       0   102.2    .045       0   122.5      .1       0
Bank Sta=102.2,122.5
XS Rating Curve= 0 ,0
Exp/Cntr(USF)=0,0
Exp/Cntr=0.3,0.1

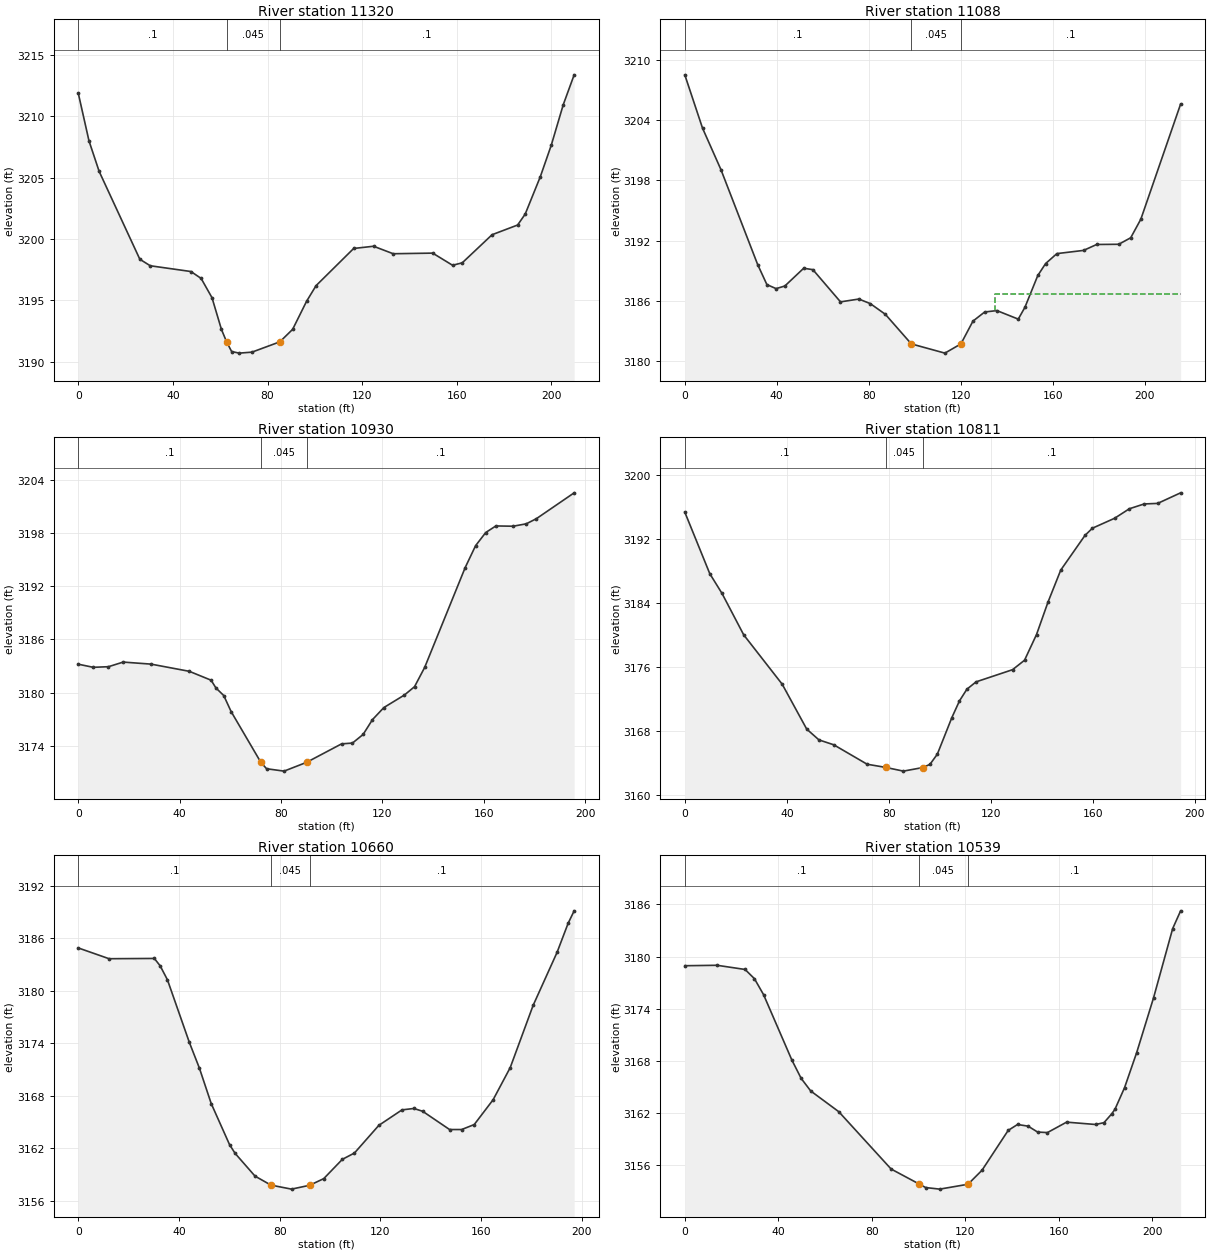
Type RM Length L Ch R = 1 ,11320   ,250.5,232.6,214
XS GIS Cut Line= 3
2168889.30313464486844.9738826612168846.80715697486951.857705274
2168819.67980566487042.434948924
#Sta/Elev= 30
       0 3211.85     4.5 3207.99     8.8  3205.5      26 3198.34    30.4 3197.81
    47.6 3197.34    51.9 3196.78    56.5 3195.21    60.5 3192.62    62.7  3191.6
    64.8 3190.82      68 3190.69    73.4 3190.77   85.18 3191.61    90.6 3192.63
    96.5 3194.92   100.5 3196.19   116.4 3199.22   124.8  3199.4   133.1 3198.79
   149.8 3198.84   158.2 3197.85   162.3 3198.05   174.9 3200.34   185.7 3201.13
   188.9 3202.02   195.3 3205.07   199.9 3207.62     205 3210.94   209.6 3213.37
#Mann= 3 ,-1,0
       0      .1       0    62.7    .045       0   85.18      .1       0
Bank Sta=62.7,85.18
XS Rating Curve= 0 ,0
Exp/Cntr(USF)=0,0
Exp/Cntr=0.3,0.1

Type RM Length L Ch R = 1 ,11088   ,139.1,157.8,172
XS GIS Cut Line= 4
2168652.82631656486857.4475586172168651.12483187486944.615066727
2168720.98451668487024.779351622 2168729.4596361487045.167119149
#Sta/Elev= 30
       0 3208.52     7.7 3203.21    15.7 3199.08    31.7  3189.6    35.7 3187.61
    39.7 3187.21    43.5 3187.47    51.7 3189.24    55.7  3189.1    67.7 3185.89
    75.7 3186.17    80.7 3185.71    87.2 3184.65    98.5  3181.7   113.1 3180.78
  120.06  3181.7   125.3 3183.97   130.4 3184.88   135.7 3185.02     145 3184.17
   147.9 3185.35   153.5 3188.52   156.9 3189.71   161.8  3190.7   173.4 3191.02
   179.1 3191.61   188.7 3191.63   193.9 3192.28   198.3 3194.13   215.6 3205.61
#Mann= 3 ,-1,0
       0      .1       0    98.5    .045       0  120.06      .1       0
#XS Ineff= 2 , 0
                             135         3186.71
Permanent Ineff=
       F       F
Bank Sta=98.5,120.06
XS Rating Curve= 0 ,0
Exp/Cntr(USF)=0,0
Exp/Cntr=0.3,0.1

Type RM Length L Ch R = 1 ,10930   ,132.7,119.2,102.7
XS GIS Cut Line= 4
2168591.04756974486895.8196219182168556.12433122486940.720928594
2168536.72253204486996.7089776592168543.37457747487075.979185741
#Sta/Elev= 30
       0  3183.2     5.9 3182.85    11.9 3182.92    17.7 3183.44    28.7 3183.21
    43.8  3182.4    52.4  3181.4    54.3 3180.53    57.4 3179.67    60.3 3177.87
   72.02 3172.16    74.3 3171.43    81.2 3171.16    90.1 3172.15   103.9 3174.23
   108.2 3174.32   112.4 3175.29   116.1 3176.96   120.6 3178.32   128.7 3179.73
   132.7 3180.67   136.7 3182.84   152.7 3194.09   156.8 3196.55   160.8 3198.03
   164.8 3198.77   171.6 3198.74   176.8 3199.01   180.8 3199.59   195.7  3202.5
#Mann= 3 ,-1,0
       0      .1       0   72.02    .045       0    90.1      .1       0
Bank Sta=72.02,90.1
XS Rating Curve= 0 ,0
Exp/Cntr(USF)=0,0
Exp/Cntr=0.3,0.1

Type RM Length L Ch R = 1 ,10811   ,150.1,150.8,150.6
XS GIS Cut Line= 2
2168403.76656044486904.8953212962168508.36256468487068.789847631
#Sta/Elev= 30
       0 3195.38     9.8 3187.69    14.6 3185.22    23.1 3180.05    38.2 3173.88
    47.8 3168.28    52.6 3166.93    58.4 3166.32    71.5 3163.89    78.7  3163.5
    85.7 3163.03    93.2 3163.47    96.1 3163.87      99 3165.14   104.7 3169.71
   107.7 3171.81   110.6 3173.26   114.2 3174.18   128.5  3175.7   133.2 3176.88
   137.9 3180.09   142.4 3184.14   147.4 3188.14   156.9 3192.47   159.8 3193.37
   168.5 3194.61   174.3  3195.8   180.1  3196.4   185.4 3196.47   194.4 3197.79
#Mann= 3 ,-1,0
       0      .1       0    78.7    .045       0    93.2      .1       0
Bank Sta=78.7,93.2
XS Rating Curve= 0 ,0
Exp/Cntr(USF)=0,0
Exp/Cntr=0.3,0.1

Type RM Length L Ch R = 1 ,10660   ,118.4,121.2,123.6
XS GIS Cut Line= 2
 2168271.9920669486976.5477021562168377.41166173487142.913000245
#Sta/Elev= 30
       0 3184.91    12.2 3183.68    30.2 3183.71    32.5 3182.87    35.4 3181.27
    44.1 3174.11    48.1 3171.16    52.8  3167.1    60.1 3162.39    62.3  3161.4
    70.2  3158.8   76.53 3157.77    84.7 3157.31    91.9 3157.75    97.5 3158.51
   104.9 3160.72   109.7 3161.44   119.4 3164.61   128.6 3166.38   133.3 3166.54
   136.8 3166.22   147.5 3164.13   152.3 3164.13   157.3  3164.7   164.8 3167.54
   171.6 3171.22   180.7 3178.34   190.2  3184.4   194.6 3187.73     197 3189.16
#Mann= 3 ,-1,0
       0      .1       0   76.53    .045       0    91.9      .1       0
Bank Sta=76.53,91.9
XS Rating Curve= 0 ,0
Exp/Cntr(USF)=0,0
Exp/Cntr=0.3,0.1

Type RM Length L Ch R = 1 ,10539   ,147,164.2,181.4
XS GIS Cut Line= 4
2168217.32456886487015.3534953882168214.55288326 487105.15610874
2168236.72636804487152.8291010132168219.54191734487220.458229586
#Sta/Elev= 30
       0 3178.94    13.8 3178.99    25.8 3178.51    29.8 3177.45    33.7 3175.62
    45.8 3168.11    49.8 3165.99    53.9 3164.54    65.9 3162.16    88.3 3155.57
  100.06 3153.88   103.1 3153.44   109.1 3153.26   121.2 3153.82   127.2 3155.43
   138.4 3160.01   142.4 3160.69   146.9  3160.5     151 3159.82   155.2 3159.76
   163.4 3160.96   175.8 3160.69   179.4  3160.9   182.7 3161.91   184.1 3162.44
   188.2 3164.92   193.4 3168.96   200.6 3175.24   208.8 3183.21   212.2 3185.25
#Mann= 3 ,-1,0
       0      .1       0  100.06    .045       0   121.2      .1       0
Bank Sta=100.06,121.2
XS Rating Curve= 0 ,0
Exp/Cntr(USF)=0,0
Exp/Cntr=0.3,0.1

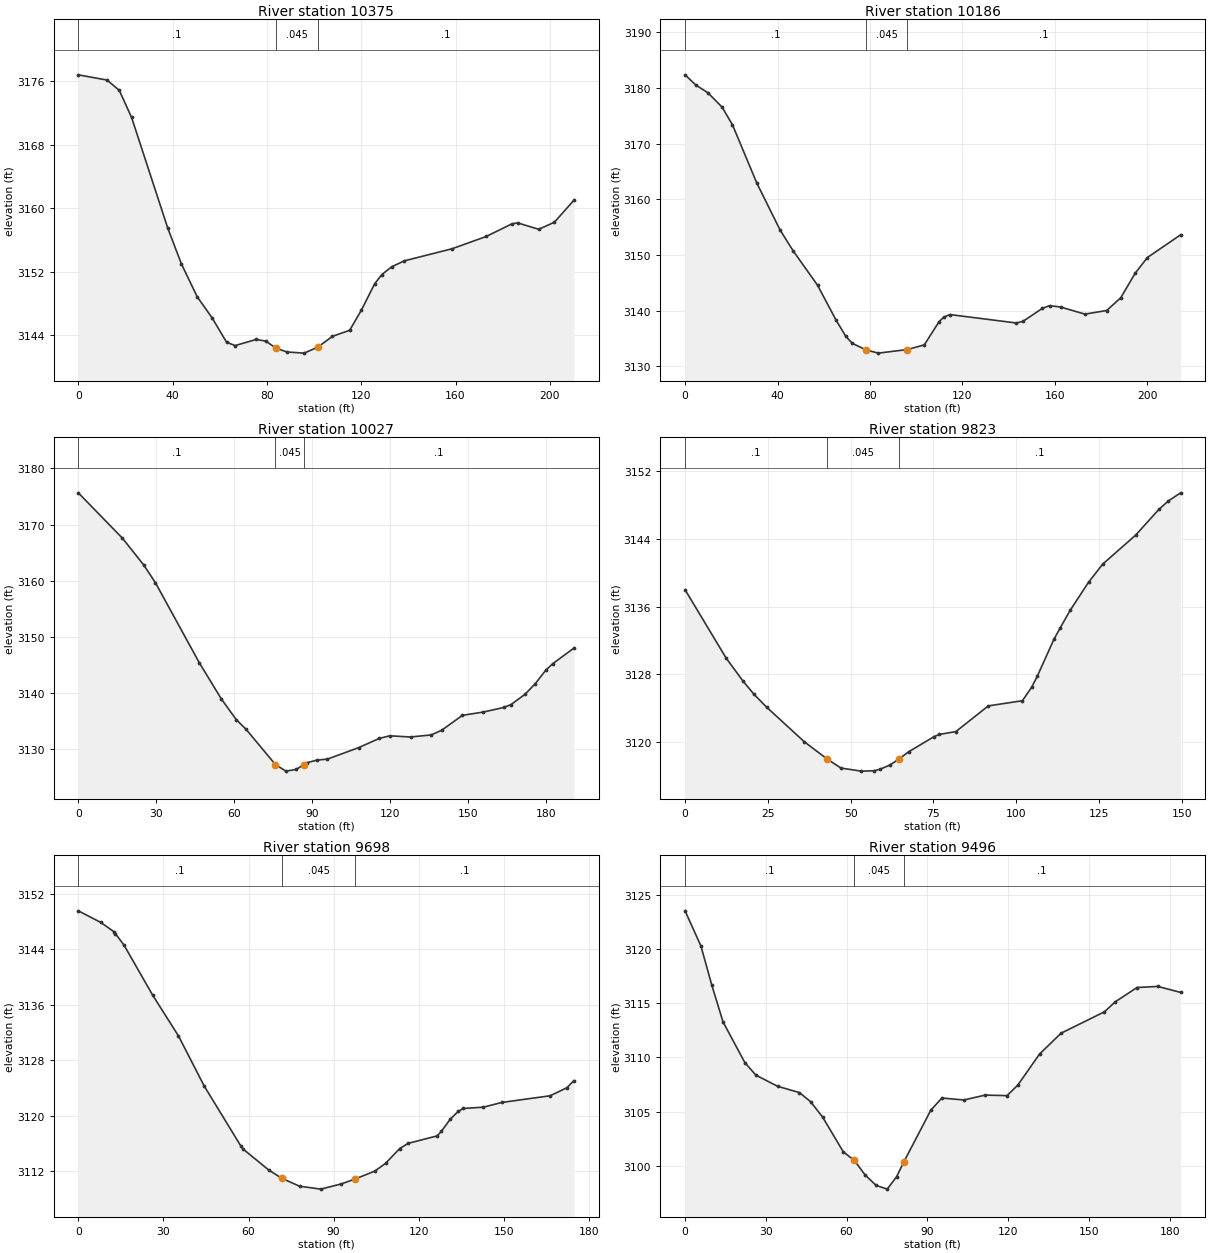
Type RM Length L Ch R = 1 ,10375   ,181.2,188.6,192.3
XS GIS Cut Line= 3
2168148.45347921486979.8420644942168099.03804414487039.140586586
2168040.56311263487158.561221353
#Sta/Elev= 30
       0 3176.84    12.2 3176.18    17.4 3174.87    22.6 3171.46    37.9 3157.54
    43.7 3153.01    50.4 3148.86    56.7 3146.21    62.9 3143.11    66.5 3142.69
    75.4 3143.46    79.5 3143.26    83.8 3142.38    88.4 3141.89    95.8 3141.74
   101.6  3142.5   107.8 3143.86   115.1 3144.62   120.1 3147.18   125.7 3150.49
   128.7 3151.63   132.9 3152.63   138.3 3153.38   158.6 3154.91     173 3156.45
   183.8 3158.03   186.3 3158.17   195.3 3157.36   201.9 3158.24   210.2 3161.02
#Mann= 3 ,-1,0
       0      .1       0    83.8    .045       0   101.6      .1       0
Bank Sta=83.8,101.6
XS Rating Curve= 0 ,0
Exp/Cntr(USF)=0,0
Exp/Cntr=0.3,0.1

Type RM Length L Ch R = 1 ,10186   ,172.2,159.1,142.6
XS GIS Cut Line= 2
2168039.73952205486858.7742485582167876.66858629486997.961057356
#Sta/Elev= 30
       0 3182.36     4.7 3180.51     9.9 3179.13      16 3176.56    20.5 3173.38
      31 3162.94    41.1 3154.47    46.8  3150.7    57.3 3144.55    65.3 3138.29
    69.5 3135.38    72.3 3134.11    78.3 3132.92    83.6 3132.34    96.1 3132.98
   103.5 3133.82   109.9 3138.01     112 3138.82   114.6 3139.27   143.3 3137.76
   146.1 3138.03   154.6 3140.39   157.7 3140.87   162.5 3140.62     173 3139.35
   182.4    3140   188.5  3142.3   194.7 3146.68     200 3149.52   214.4 3153.61
#Mann= 3 ,-1,0
       0      .1       0    78.3    .045       0    96.1      .1       0
Bank Sta=78.3,96.1
XS Rating Curve= 0 ,0
Exp/Cntr(USF)=0,0
Exp/Cntr=0.3,0.1

Type RM Length L Ch R = 1 ,10027   ,195.4,204.4,213.6
XS GIS Cut Line= 3
2167874.46970478486801.5284433232167827.54476753486845.907943938
2167826.82496624486972.085695435
#Sta/Elev= 30
       0 3175.65      17 3167.56    25.2 3162.79    29.7 3159.63    46.6 3145.37
    55.1 3138.91    60.8 3135.27    64.6 3133.52    75.9 3127.25    79.9 3126.08
    83.9 3126.38   86.71  3127.2    87.9 3127.57    91.9 3128.04    95.9 3128.22
   107.9 3130.26   115.9 3131.91   119.9 3132.37   127.9 3132.16   135.9 3132.53
   139.9 3133.36   147.9 3136.02   155.9  3136.6   163.9 3137.43   166.6 3137.94
   171.9 3139.73   175.9 3141.64   179.9 3144.01   182.6  3145.2   190.8 3147.99
#Mann= 3 ,-1,0
       0      .1       0    75.9    .045       0   86.71      .1       0
Bank Sta=75.9,86.71
XS Rating Curve= 0 ,0
Exp/Cntr(USF)=0,0
Exp/Cntr=0.3,0.1

Type RM Length L Ch R = 1 ,9823    ,117.9,124.7,133
XS GIS Cut Line= 2
2167672.41812131486759.1197878222167584.29392876486880.187603758
#Sta/Elev= 30
       0 3137.99    12.4 3129.91    17.4 3127.24    20.8 3125.63    24.6 3124.11
      36 3120.01   42.983117.943    47.1 3116.89    53.2 3116.53      57 3116.57
    58.9 3116.75    61.8 3117.24    64.6 3117.95    67.5 3118.81    75.2 3120.61
    76.8 3120.87    81.8 3121.21    91.6 3124.25   101.9 3124.86   104.7 3126.46
   106.4 3127.76   111.4 3132.11   113.3 3133.46   116.3 3135.54   121.9 3138.89
   126.2 3141.04   136.1 3144.45   143.1 3147.49     146  3148.5   149.7 3149.46
#Mann= 3 ,-1,0
       0      .1       0   42.98    .045       0    64.6      .1       0
Bank Sta=42.98,64.6
XS Rating Curve= 0 ,0
Exp/Cntr(USF)=0,0
Exp/Cntr=0.3,0.1

Type RM Length L Ch R = 1 ,9698    ,213.8,201.6,186.8
XS GIS Cut Line= 2
2167627.12063916486674.2899576082167473.93279043486758.296197237
#Sta/Elev= 30
       0 3149.52     7.9 3147.85    12.5 3146.53    13.1 3146.21    16.1 3144.59
    26.2 3137.38    35.3  3131.5    44.4 3124.26    57.3 3115.63    58.1 3115.19
    67.2 3112.15    71.8 3110.97      78 3109.84    85.5 3109.42    92.7 3110.17
    97.5 3110.87   104.5 3112.01   108.3 3113.13   113.3 3115.27   116.3 3116.02
   126.5 3117.09     128 3117.75   131.1 3119.49   133.9 3120.61   135.7 3121.04
   142.8 3121.23   149.3 3121.91   166.3 3122.87   172.2 3124.02   174.7 3125.05
#Mann= 3 ,-1,0
       0      .1       0    71.8    .045       0    97.5      .1       0
Bank Sta=71.8,97.5
XS Rating Curve= 0 ,0
Exp/Cntr(USF)=0,0
Exp/Cntr=0.3,0.1

Type RM Length L Ch R = 1 ,9496    ,118.9,121.1,123.3
XS GIS Cut Line= 3
2167441.81275763 486515.336974782167423.83578362486613.177640848
 2167432.7532612486697.350493977
#Sta/Elev= 30
       0 3123.51     5.9 3120.26     9.9 3116.68    14.1 3113.27    22.2 3109.52
    26.3 3108.36    34.4 3107.33    42.5 3106.75    46.6 3105.92    51.1 3104.49
    58.8 3101.28    62.9 3100.49    66.9 3099.15      71 3098.19    75.1 3097.85
    78.6    309981.187773100.324    91.3 3105.13    95.4 3106.25   103.6 3106.07
   111.5 3106.52   119.6 3106.47   123.6 3107.44   131.7 3110.31   139.7 3112.23
   155.8  3114.2   159.8 3115.12   167.9 3116.44   175.6 3116.54   184.1 3115.99
#Mann= 3 ,-1,0
       0      .1       0    62.9    .045       081.18777      .1       0
Bank Sta=62.9,81.18777
XS Rating Curve= 0 ,0
Exp/Cntr(USF)=0,0
Exp/Cntr=0.3,0.1

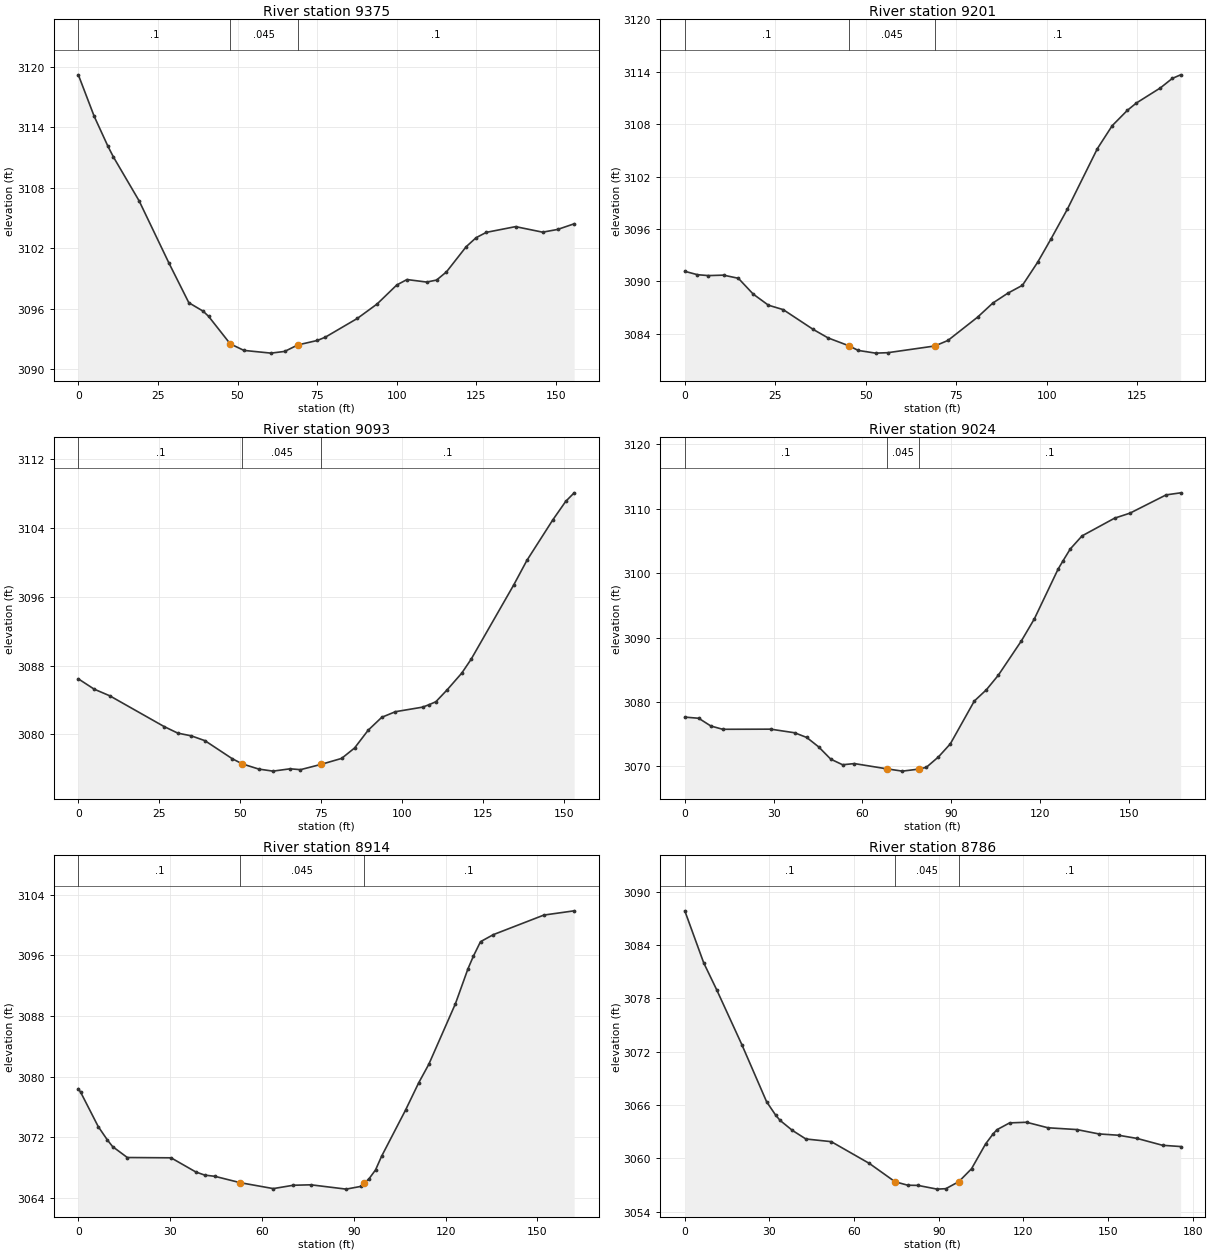
Type RM Length L Ch R = 1 ,9375    ,174.4,173.9,171.9
XS GIS Cut Line= 2
2167347.99948149486472.4507204742167293.92587667486618.495281943
#Sta/Elev= 30
       0 3119.19       5 3115.06     9.3  3112.1      11 3111.05    19.1 3106.68
    28.4 3100.55    34.7 3096.58    39.2 3095.74    40.9 3095.23    47.7  3092.5
      52 3091.85    60.5 3091.58    64.8 3091.75    68.9 3092.39    75.1 3092.84
    77.6 3093.17    87.6 3095.02    93.8 3096.45     100 3098.34   103.2 3098.88
   109.4 3098.63   112.5 3098.83   115.6 3099.64   121.8 3102.14   124.9 3103.03
   128.1 3103.56   137.3 3104.13   145.8 3103.58   150.5 3103.85   155.7 3104.41
#Mann= 3 ,-1,0
       0      .1       0    47.7    .045       0    68.9      .1       0
Bank Sta=47.7,68.9
XS Rating Curve= 0 ,0
Exp/Cntr(USF)=0,0
Exp/Cntr=0.3,0.1

Type RM Length L Ch R = 1 ,9201    ,107.6,108.7,109.6
XS GIS Cut Line= 2
2167174.14581763486442.8610033352167139.55501308486575.459087456
#Sta/Elev= 30
       0 3091.16     3.5 3090.77     6.5 3090.67    10.7 3090.72    14.8 3090.36
    18.9 3088.55    23.1 3087.28    27.2 3086.77    35.5  3084.5    39.6 3083.53
   45.41 3082.62    47.9  3082.1    52.7 3081.79    56.1 3081.84    69.1 3082.61
    72.7 3083.24    80.9 3085.91    85.1 3087.52    89.2 3088.64    93.3 3089.56
    97.5  3092.2   101.2 3094.88   105.7 3098.27     114 3105.21   118.1 3107.84
   122.3  3109.6   124.8 3110.44   131.4 3112.16   134.7 3113.25     137 3113.66
#Mann= 3 ,-1,0
       0      .1       0   45.41    .045       0    69.1      .1       0
Bank Sta=45.41,69.1
XS Rating Curve= 0 ,0
Exp/Cntr(USF)=0,0
Exp/Cntr=0.3,0.1

Type RM Length L Ch R = 1 ,9093    ,70.9,68.7,64.1
XS GIS Cut Line= 3
2167077.06115654486403.9117283272167044.21154946486507.251117263
2167040.10534858486551.734960182
#Sta/Elev= 30
       0 3086.47     4.9 3085.27     9.7  3084.5    26.5 3080.92    30.7 3080.16
    34.9 3079.84    39.1 3079.28    47.5 3077.19   50.64 3076.58    55.7 3075.98
    60.1 3075.74    65.4 3076.01    68.6 3075.91      75 3076.53    81.3 3077.22
    85.3 3078.43    89.5  3080.5    93.7    3082    97.9 3082.65   106.3 3083.18
   108.4 3083.48   110.4 3083.81   113.9  3085.2   118.4 3087.14   121.3 3088.76
   134.5 3097.43   138.5 3100.24   146.5 3104.95   150.5 3107.11   153.1  3108.1
#Mann= 3 ,-1,0
       0      .1       0   50.64    .045       0      75      .1       0
Bank Sta=50.64,75
XS Rating Curve= 0 ,0
Exp/Cntr(USF)=0,0
Exp/Cntr=0.3,0.1

Type RM Length L Ch R = 1 ,9024    ,94.3,109.9,116.1
XS GIS Cut Line= 2
2167001.19179486486388.5040247522166975.66048674486554.045732256
#Sta/Elev= 30
       0 3077.66     4.7 3077.48     8.8 3076.28    12.8 3075.77      29 3075.79
    37.1 3075.23    41.2  3074.5    45.2 3073.05    49.3 3071.14    53.3 3070.27
    57.3 3070.45   68.47 3069.62    73.5 3069.28   79.16  3069.6    81.6 3069.87
    85.7 3071.49    89.7 3073.51    97.8 3080.15   101.9 3081.91   105.9 3084.15
   113.7 3089.48   118.1 3092.91   126.1 3100.61   127.7 3101.85   130.2 3103.73
   134.2 3105.77   145.2 3108.52   150.4  3109.3   162.6 3112.13   167.5 3112.45
#Mann= 3 ,-1,0
       0      .1       0   68.47    .045       0   79.16      .1       0
Bank Sta=68.47,79.16
XS Rating Curve= 0 ,0
Exp/Cntr(USF)=0,0
Exp/Cntr=0.3,0.1

Type RM Length L Ch R = 1 ,8914    ,129.5,128,126.8
XS GIS Cut Line= 3
2166927.86919106486371.7464880632166869.69801186486461.398540715
2166856.01067558486514.779152218
#Sta/Elev= 30
       0  3078.4      .8 3077.91     6.5 3073.41     9.5 3071.64    11.2 3070.77
      16 3069.33    30.3 3069.29    38.4 3067.42    41.3 3067.01    44.6 3066.85
    52.9 3066.01    63.7 3065.23    70.2 3065.67      76 3065.73    87.5 3065.16
    92.3 3065.52    93.4 3065.94      95 3066.54    97.1 3067.69    99.1 3069.51
   106.9 3075.58   111.2 3079.18   114.5 3081.62   123.2 3089.61   127.3 3094.22
   129.1 3095.91   131.4  3097.8   135.6 3098.73   152.1 3101.31     162 3101.87
#Mann= 3 ,-1,0
       0      .1       0    52.9    .045       0    93.4      .1       0
Bank Sta=52.9,93.4
XS Rating Curve= 0 ,0
Exp/Cntr(USF)=0,0
Exp/Cntr=0.3,0.1

Type RM Length L Ch R = 1 ,8786    ,81.6,72.8,60
XS GIS Cut Line= 2
2166821.64904742486287.2023828462166740.11357955486442.861003335
#Sta/Elev= 30
       0 3087.85     6.7    3082    11.3 3078.97    20.2 3072.81      29 3066.37
    32.2 3064.87    33.8 3064.27    38.1 3063.16    42.9 3062.19    51.9 3061.89
    65.4 3059.44    74.5 3057.38      79 3056.99    82.6 3056.97    89.4 3056.55
    92.5  3056.6    97.1 3057.39   101.6 3058.84   106.6 3061.64   109.2 3062.74
   110.6 3063.23   115.1    3064   121.1 3064.07   128.7 3063.45   138.9 3063.25
   146.7 3062.76   153.7 3062.61   160.3 3062.25   169.3 3061.48   175.7 3061.34
#Mann= 3 ,-1,0
       0      .1       0    74.5    .045       0    97.1      .1       0
Bank Sta=74.5,97.1
XS Rating Curve= 0 ,0
Exp/Cntr(USF)=0,0
Exp/Cntr=0.3,0.1

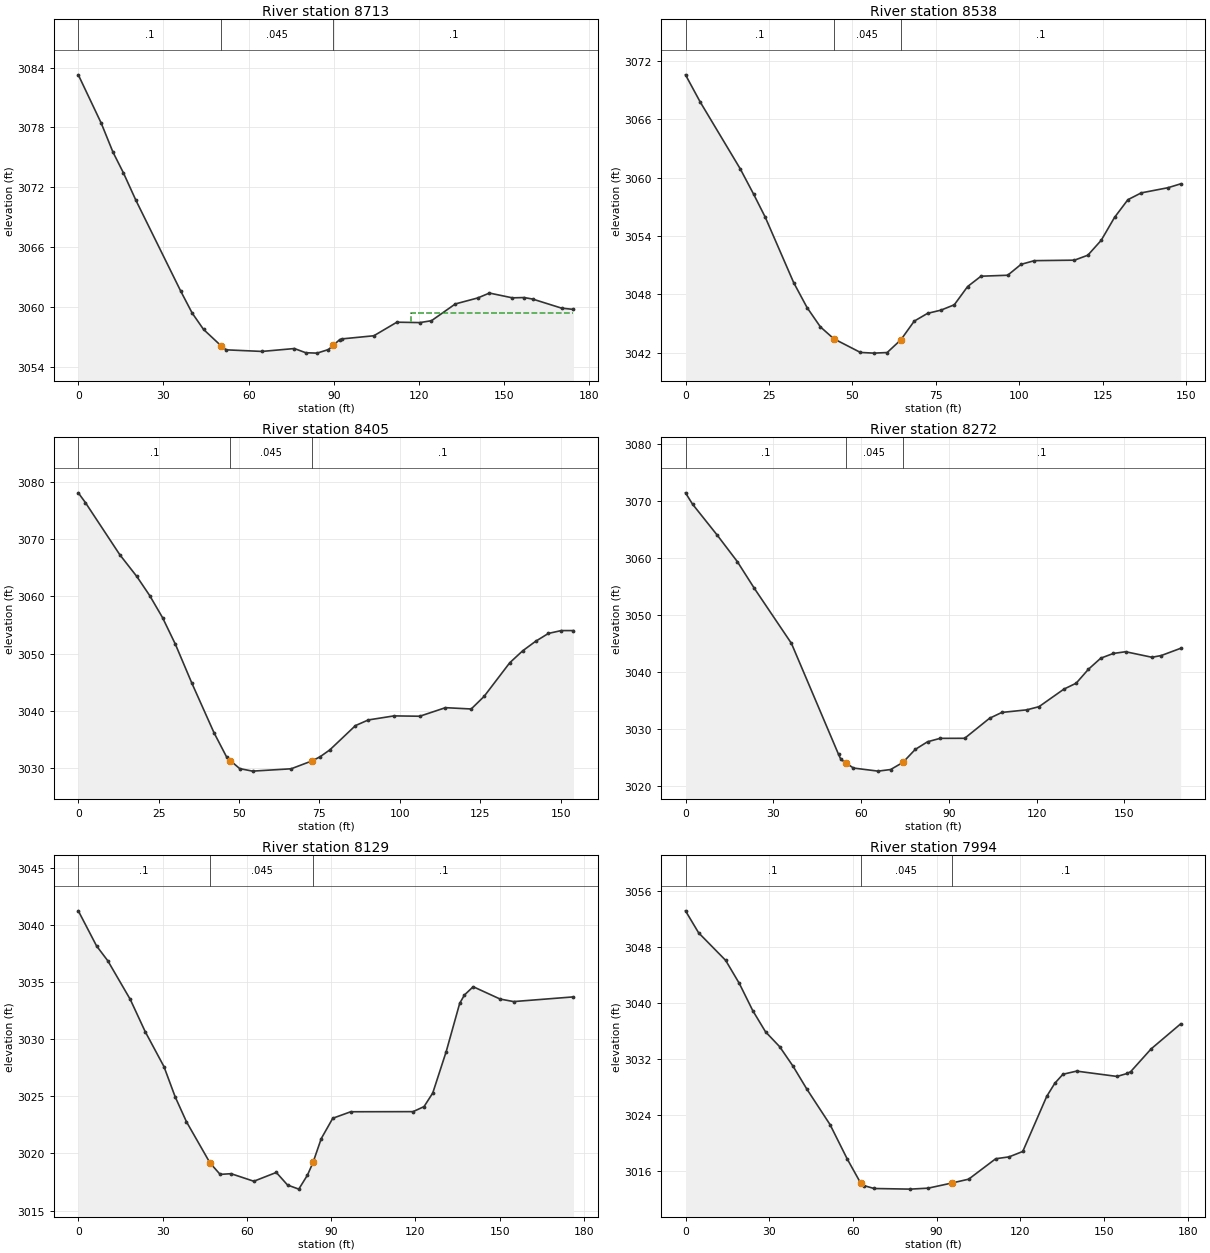
Type RM Length L Ch R = 1 ,8713    ,175.8,175.6,156
XS GIS Cut Line= 3
2166716.12372137486269.1058664962166715.08871408486377.221422576
2166728.09168354486442.236269919
#Sta/Elev= 30
       0 3083.27     8.1 3078.41    12.2 3075.53    15.9 3073.44    20.3 3070.69
    36.1 3061.58    40.1  3059.4    44.1 3057.7650.18747 3056.14    52.1 3055.71
    64.7 3055.55    76.1 3055.84    80.1 3055.42    84.1 3055.38    88.1 3055.74
   89.76 3056.16    92.1 3056.74      93 3056.81   104.1 3057.12   112.2 3058.48
   120.3 3058.44   124.4 3058.63   132.8 3060.31   140.7 3060.91   144.8  3061.4
   152.9 3060.92     157 3060.95     160  3060.8   170.2 3059.89   174.4 3059.76
#Mann= 3 ,-1,0
       0      .1       050.18747    .045       0   89.76      .1       0
#XS Ineff= 2 , 0
                          117.07         3059.36
Permanent Ineff=
       F       F
Bank Sta=50.18747,89.76
XS Rating Curve= 0 ,0
Exp/Cntr(USF)=0,0
Exp/Cntr=0.3,0.1

Type RM Length L Ch R = 1 ,8538    ,132.1,132.2,131
XS GIS Cut Line= 2
2166581.16059672486368.7378507212166578.68982496486516.984155949
#Sta/Elev= 30
       0 3070.59     4.4  3067.8    16.4 3060.92    20.4 3058.32    23.9 3055.94
    32.4 3049.22    36.4 3046.66    40.4 3044.67    44.4 3043.45    52.4 3042.04
    56.4 3041.97    60.4 3042.03    64.5 3043.34    68.5 3045.26    72.5 3046.06
    76.5 3046.39    80.5 3046.94    84.5 3048.82    88.5 3049.88    96.5 3049.98
   100.5  3051.1   104.5 3051.48   116.5 3051.53   120.5 3052.04   124.5 3053.57
   128.5 3055.93   132.5 3057.75   136.5 3058.45   144.5 3058.98   148.3 3059.38
#Mann= 3 ,-1,0
       0      .1       0    44.4    .045       0    64.5      .1       0
Bank Sta=44.4,64.5
XS Rating Curve= 0 ,0
Exp/Cntr(USF)=0,0
Exp/Cntr=0.3,0.1

Type RM Length L Ch R = 1 ,8405    ,137.5,133.7,127.2
XS GIS Cut Line= 2
 2166450.8655216486343.0030818692166451.54988842486496.985615051
#Sta/Elev= 30
       0 3078.16     2.2 3076.46    12.9 3067.32    18.2  3063.5    22.2 3060.16
    26.2 3056.29    30.2 3051.62    35.3 3044.83    42.2 3036.13    46.2 3031.79
    47.3 3031.23    50.2 3029.83    54.2 3029.39    66.2  3029.8   72.833031.217
    75.2 3031.91    78.2  3033.1    86.2 3037.37    90.2 3038.36    98.2 3039.07
   106.2 3039.01   114.2 3040.51   122.2 3040.28   126.2 3042.48   134.2 3048.39
   138.2 3050.47   142.2 3052.13   146.2 3053.52   150.2 3054.02     154 3054.02
#Mann= 3 ,-1,0
       0      .1       0    47.3    .045       0   72.83      .1       0
Bank Sta=47.3,72.83
XS Rating Curve= 0 ,0
Exp/Cntr(USF)=0,0
Exp/Cntr=0.3,0.1

Type RM Length L Ch R = 1 ,8272    ,137.4,142.3,149.3
XS GIS Cut Line= 2
2166299.98677114  486354.90152892166354.83790407486515.007538546
#Sta/Elev= 30
       0 3071.41     2.4 3069.43    10.9 3063.96    17.7 3059.37    23.5  3054.7
    36.2 3045.04    52.3  3025.6    53.1 3024.72    54.8  3024.1    57.4 3023.21
    65.8 3022.67    70.1 3022.95    74.3  3024.2    78.5 3026.47    82.7 3027.81
      87 3028.41    95.4 3028.42   103.9 3031.93   108.1 3032.95   116.6  3033.4
   120.8 3033.96   129.3 3037.03   133.5 3038.07   137.7 3040.52   141.9 3042.45
   146.2 3043.28   150.4 3043.58   159.4 3042.61   162.6 3042.92   169.2 3044.18
#Mann= 3 ,-1,0
       0      .1       0    54.8    .045       0    74.3      .1       0
Bank Sta=54.8,74.3
XS Rating Curve= 0 ,0
Exp/Cntr(USF)=0,0
Exp/Cntr=0.3,0.1

Type RM Length L Ch R = 1 ,8129    ,145.1,135,118.3
XS GIS Cut Line= 3
2166181.90936365486382.6963570892166186.01556453486487.404479653
2166225.70883975486546.944392483
#Sta/Elev= 30
       0 3041.23     6.5 3038.16    10.5 3036.86    18.5 3033.48    23.8 3030.67
    30.5  3027.6    34.5 3024.95    38.5 3022.78    46.9 3019.17    50.5 3018.17
    54.4 3018.23    62.5 3017.57    70.5 3018.34    74.5 3017.24    78.5 3016.88
    81.6 3018.11    83.6 3019.23    86.5  3021.3    90.6 3023.08      97 3023.65
   119.2 3023.66   123.1  3024.1   126.2 3025.29     131 3028.92   135.8 3033.14
   137.5 3033.87   140.6 3034.59   150.2 3033.51     155 3033.29   176.3  3033.7
#Mann= 3 ,-1,0
       0      .1       0    46.9    .045       0    83.6      .1       0
Bank Sta=46.9,83.6
XS Rating Curve= 0 ,0
Exp/Cntr(USF)=0,0
Exp/Cntr=0.3,0.1

Type RM Length L Ch R = 1 ,7994    ,139,144.8,151.9
XS GIS Cut Line= 2
2166036.15942235486457.2599249642166136.03771294486603.979433335
#Sta/Elev= 30
       0 3053.22     4.7 3050.08    14.4 3046.14    19.3 3042.84    24.1 3038.97
    28.7 3035.93    33.8 3033.79    38.6 3030.99    43.5 3027.75    51.8 3022.69
      58 3017.75    62.8 3014.32      64 3013.96    67.6 3013.55    80.6 3013.46
      87  3013.6   95.45 3014.33   101.5 3014.88   111.2  3017.8     116 3018.07
   120.9 3018.84   129.5 3026.72   132.4 3028.59   135.3 3029.87   140.2 3030.32
   154.7 3029.56   158.3 3029.98   159.6 3030.25   166.9 3033.49   177.5 3037.07
#Mann= 3 ,-1,0
       0      .1       0    62.8    .045       0   95.45      .1       0
Bank Sta=62.8,95.45
XS Rating Curve= 0 ,0
Exp/Cntr(USF)=0,0
Exp/Cntr=0.3,0.1