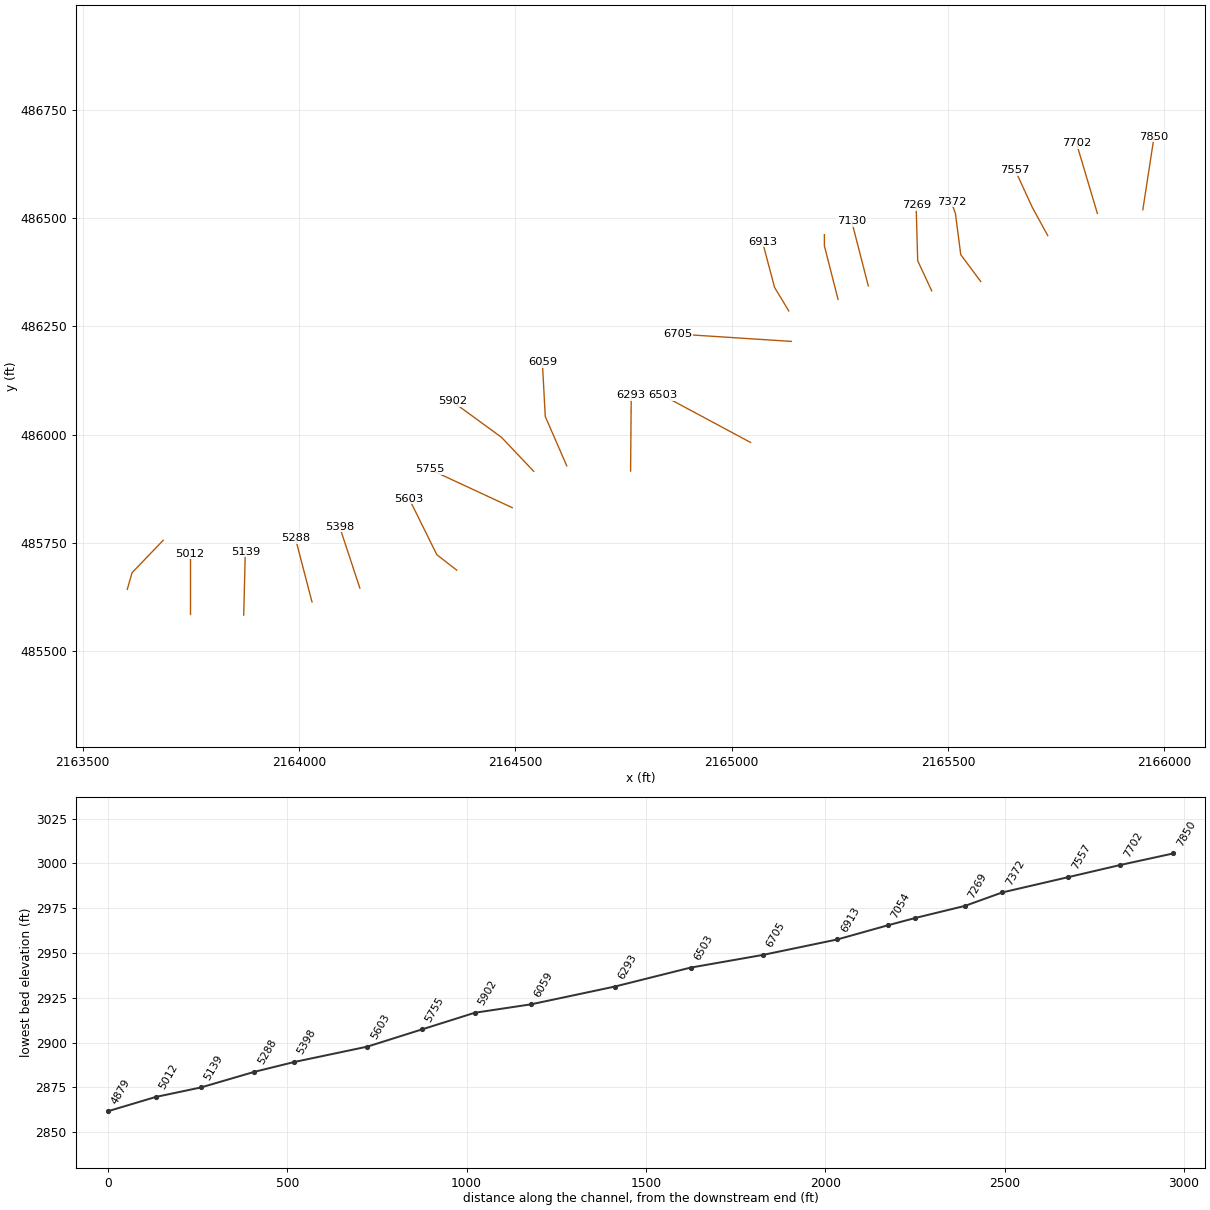
HEC-RAS study BEECHYRN.prj: BEECHYRN

--- BEECHYRN.g01 (geometry) --- (continued)

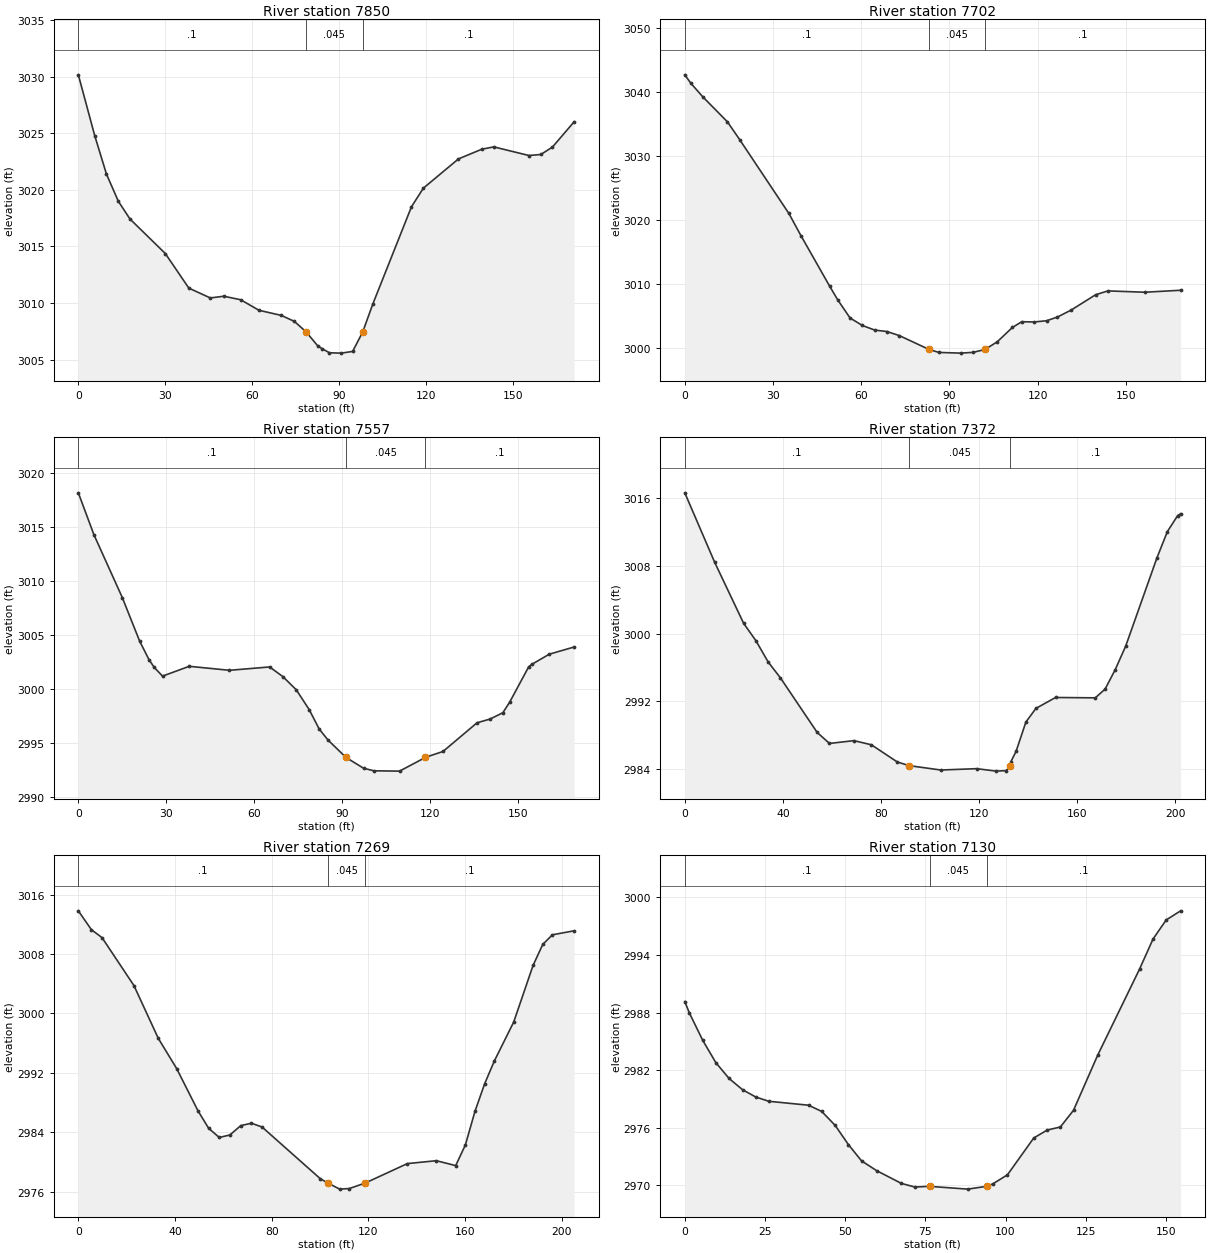
Type RM Length L Ch R = 1 ,7850    ,140.1,148,154.7
XS GIS Cut Line= 2
2165949.90901365486519.5697199172165975.91495259 486688.60832301
#Sta/Elev= 30
       0 3030.15     5.7 3024.74     9.7 3021.39    13.8 3018.99    17.8 3017.43
      30 3014.38    38.1 3011.33    45.5 3010.46    50.2 3010.61      56  3010.3
    62.3 3009.37      70 3008.92    74.5 3008.39    78.5 3007.48    82.6 3006.22
    84.1 3005.98    86.6 3005.62    90.7 3005.59    94.6 3005.74    98.1 3007.47
   101.6 3009.95   114.9 3018.51     119 3020.15   131.1 3022.73   139.2 3023.59
   143.3 3023.79   155.4 3023.03   159.5 3023.12   163.5 3023.77     171 3026.01
#Mann= 3 ,-1,0
       0      .1       0    78.5    .045       0    98.1      .1       0
Bank Sta=78.5,98.1
XS Rating Curve= 0 ,0
Exp/Cntr(USF)=0,0
Exp/Cntr=0.3,0.1

Type RM Length L Ch R = 1 ,7702    ,141.7,144.6,147.9
XS GIS Cut Line= 2
2165844.87061409486511.3013809162165796.69056489486672.889853614
#Sta/Elev= 30
       0 3042.65     2.1 3041.31     6.1 3039.22    14.5  3035.3    18.7 3032.49
    35.4 3020.97    39.5  3017.5    49.3 3009.57      52 3007.47    56.2 3004.63
    60.4 3003.46    64.6 3002.74    68.7 3002.52    72.9 3001.89   83.03 2999.72
    86.4 2999.25    93.8 2999.14      98 2999.26   102.1 2999.71   106.3 3000.93
   111.4 3003.16   114.6 3004.05   118.8 3004.01     123  3004.2   126.7 3004.78
   131.4 3005.88   139.7 3008.27   143.9 3008.87   156.4 3008.66   168.6 3008.97
#Mann= 3 ,-1,0
       0      .1       0   83.03    .045       0   102.1      .1       0
Bank Sta=83.03,102.1
XS Rating Curve= 0 ,0
Exp/Cntr(USF)=0,0
Exp/Cntr=0.3,0.1

Type RM Length L Ch R = 1 ,7557    ,200,184.8,179.5
XS GIS Cut Line= 3
2165730.22726631486460.0298070872165694.64019198486525.044654431
2165654.94691676486611.274873012
#Sta/Elev= 30
       0 3018.16     5.3 3014.29      15 3008.45    20.9 3004.42    24.1  3002.7
    25.9 3001.98    28.7 3001.18    37.8 3002.09    51.5 3001.72    65.2 3002.03
    69.7 3001.14    74.3 2999.91    78.7 2998.07    82.1 2996.28    85.1 2995.26
   91.22 2993.65    97.2 2992.65   100.7 2992.41   109.5 2992.38   118.3 2993.65
   118.3 2993.66   124.3  2994.2   135.9 2996.86   140.3  2997.2   144.7 2997.79
     147 2998.76   153.5 3002.04   154.5 3002.26   160.5 3003.21     169 3003.88
#Mann= 3 ,-1,0
       0      .1       0   91.22    .045       0   118.3      .1       0
Bank Sta=91.22,118.3
XS Rating Curve= 0 ,0
Exp/Cntr(USF)=0,0
Exp/Cntr=0.3,0.1

Type RM Length L Ch R = 1 ,7372    ,103.4,103.5,98.7
XS GIS Cut Line= 4
2165575.47793641486353.9159980422165529.26552104 486415.82007581
2165516.93477369486510.9022131132165507.17363435486538.257682064
#Sta/Elev= 30
       0 3016.57    12.2 3008.38      24  3001.2      29 2999.16      34 2996.65
      39 2994.78      54 2988.35      59 2987.06      69 2987.39    76.1  2986.9
    86.7 2984.8791.540772984.444   104.4 2983.93     119 2984.09     127  2983.8
   131.1 2983.86  132.68 2984.37     133 2984.92   135.1 2986.13   139.1 2989.58
   143.2 2991.19   151.2 2992.47   167.4 2992.43   171.4 2993.46   175.5 2995.73
   179.8 2998.52   192.5 3008.88   196.8 3012.01     201 3013.89   202.2 3014.11
#Mann= 3 ,-1,0
       0      .1       091.54077    .045       0  132.68      .1       0
Bank Sta=91.54077,132.68
XS Rating Curve= 0 ,0
Exp/Cntr(USF)=0,0
Exp/Cntr=0.3,0.1

Type RM Length L Ch R = 1 ,7269    ,133.8,138.3,145.4
XS GIS Cut Line= 3
2165462.15708293486332.286135298 2165429.7506153486401.939937174
2165426.07536257486530.183349017
#Sta/Elev= 30
       0 3013.83     5.4 3011.29     9.8 3010.22      23 3003.76    33.1 2996.63
    40.7 2992.56    49.5 2986.88    53.9 2984.53    58.3 2983.29    62.7 2983.63
    67.2 2984.89    71.6 2985.21      76  2984.7   100.1 2977.73   103.3 2977.14
   108.1 2976.33   112.1 2976.41118.67822977.153   136.1 2979.77   148.1 2980.16
   156.1  2979.5   160.1 2982.28   164.1 2986.84   168.1 2990.55   172.1 2993.61
   180.1 2998.85   188.1 3006.47   192.1  3009.3   196.1  3010.6   205.1 3011.14
#Mann= 3 ,-1,0
       0      .1       0   103.3    .045       0118.6782      .1       0
Bank Sta=103.3,118.6782
XS Rating Curve= 0 ,0
Exp/Cntr(USF)=0,0
Exp/Cntr=0.3,0.1

Type RM Length L Ch R = 1 ,7130    ,76,76.7,76.2
XS GIS Cut Line= 2
2165315.63130442486343.7830560082165277.08726506486493.511824288
#Sta/Elev= 30
       0 2989.15     1.4 2987.98     5.6  2985.1     9.7 2982.77    13.8 2981.13
      18 2979.96    22.1  2979.2    26.2 2978.75    38.6 2978.34    42.7 2977.69
    46.9 2976.23      51 2974.24    55.1 2972.54    59.8 2971.52    67.5 2970.19
    71.7 2969.81    76.3 2969.88    88.2 2969.59    94.1 2969.88      96 2970.13
   100.6 2971.08   108.8 2974.92     113 2975.75   117.1 2976.07   121.2 2977.81
   128.8  2983.6   141.8 2992.54     146 2995.67   150.1 2997.66   154.6 2998.61
#Mann= 3 ,-1,0
       0      .1       0    76.3    .045       0    94.1      .1       0
Bank Sta=76.3,94.1
XS Rating Curve= 0 ,0
Exp/Cntr(USF)=0,0
Exp/Cntr=0.3,0.1

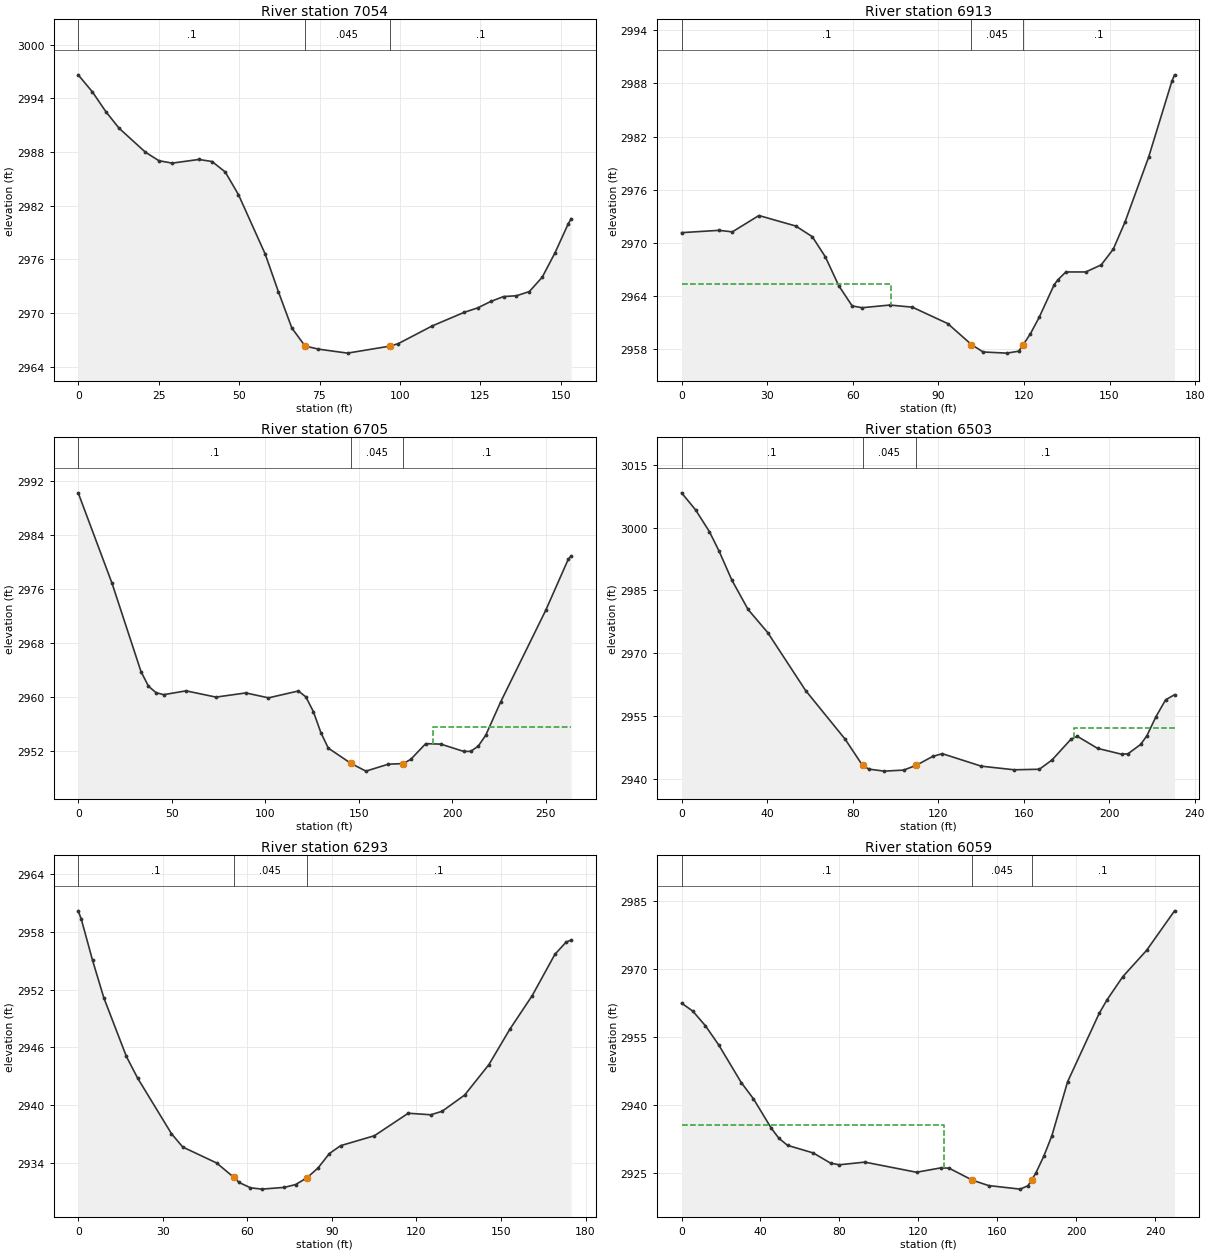
Type RM Length L Ch R = 1 ,7054    ,140.3,141.1,137.3
XS GIS Cut Line= 3
 2165245.6955619486312.8909420472165214.21468845486436.076968592
2165214.21468845486462.082907529
#Sta/Elev= 30
       0 2996.64     4.4 2994.74     8.6 2992.52    12.7 2990.67    20.9 2987.98
    25.1 2987.03    29.2 2986.76    37.5 2987.17    41.6 2986.94    45.7 2985.77
    49.8 2983.24    58.1  2976.6    62.2 2972.39    66.4 2968.31    70.5  2966.3
    74.6 2965.95    83.7  2965.5    96.8 2966.28    99.4 2966.55     110 2968.54
     120 2970.07   124.2 2970.57   128.2 2971.28   132.2 2971.83   136.2 2971.92
   140.2 2972.39   144.2 2973.99   148.2 2976.74   152.2  2979.9   153.2 2980.55
#Mann= 3 ,-1,0
       0      .1       0    70.5    .045       0    96.8      .1       0
Bank Sta=70.5,96.8
XS Rating Curve= 0 ,0
Exp/Cntr(USF)=0,0
Exp/Cntr=0.3,0.1

Type RM Length L Ch R = 1 ,6913    ,186.3,207.3,226.4
XS GIS Cut Line= 3
2165131.80588594486285.9669969692165098.99612238 486340.42475962
2165071.00752987486446.042154246
#Sta/Elev= 30
       0 2971.17    13.1 2971.43    17.8 2971.26    27.1  2973.1      40 2971.92
    45.8 2970.72    50.4 2968.44    55.1 2965.19    59.8 2962.91    63.3 2962.71
      73 2963.01    80.9 2962.77    93.3 2960.92   101.6 2958.56   105.7 2957.72
     114 2957.59   118.2 2957.81  119.722958.521   122.3 2959.79   125.4 2961.66
   130.6  2965.3   131.9 2965.85   134.7 2966.74   141.7 2966.74   147.1 2967.54
   151.3  2969.3   155.4 2972.34   163.7 2979.67   171.9 2988.27   172.8 2988.96
#Mann= 3 ,-1,0
       0      .1       0   101.6    .045       0  119.72      .1       0
#XS Ineff= 2 , 0
           73.52 2965.39
Permanent Ineff=
       F       F
Bank Sta=101.6,119.72
XS Rating Curve= 0 ,0
Exp/Cntr(USF)=0,0
Exp/Cntr=0.3,0.1

Type RM Length L Ch R = 1 ,6705    ,208.8,202.1,193.6
XS GIS Cut Line= 2
2165137.73573815486215.5500019862164874.59854637486232.598327087
#Sta/Elev= 30
       0 2990.28    18.1 2976.85    33.6 2963.74    37.6 2961.57    41.6 2960.62
    45.7 2960.31    57.7 2960.88    73.7 2959.95    89.7 2960.57   101.8 2959.84
   117.8 2960.86   121.8 2959.98   125.8  2957.8   129.8 2954.69   133.8 2952.37
   145.9 2950.11   153.9 2948.96   165.9 2949.99   173.9 2950.08   177.9 2950.71
   185.9 2953.04     194 2952.97   206.3 2951.88     210  2951.9     214 2952.67
     218 2954.29     226 2959.24   250.1 2972.84   262.1 2980.39   263.7 2980.91
#Mann= 3 ,-1,0
       0      .1       0   145.9    .045       0   173.9      .1       0
#XS Ineff= 2 , 0
                           189.8         2955.46
Permanent Ineff=
       F       F
Bank Sta=145.9,173.9
XS Rating Curve= 0 ,0
Exp/Cntr(USF)=0,0
Exp/Cntr=0.3,0.1

Type RM Length L Ch R = 1 ,6503    ,226.3,210.4,187.4
XS GIS Cut Line= 2
2165043.59933433485982.0620712522164840.50189617486091.023105594
#Sta/Elev= 30
       0 3008.32     6.6 3004.22      13 2999.06    17.5 2994.44    23.5 2987.49
    31.1 2980.46    40.3 2974.93      58 2961.11    76.5 2949.47    84.6 2943.24
    87.6 2942.34    94.7 2941.86   103.8  2942.1  109.732943.252   117.4 2945.37
   121.9 2946.03   140.1 2943.05   155.5 2942.18   167.3 2942.31   173.2 2944.52
   182.1  2949.5     185 2950.19   194.5  2947.3   205.7  2945.9   208.7 2945.99
   214.6 2948.22   217.5 2950.25   221.8 2954.85   226.3 2958.88   230.5 2960.11
#Mann= 3 ,-1,0
       0      .1       0    84.6    .045       0  109.73      .1       0
#XS Ineff= 2 , 0
                          183.56          2952.1
Permanent Ineff=
       F       F
Bank Sta=84.6,109.73
XS Rating Curve= 0 ,0
Exp/Cntr(USF)=0,0
Exp/Cntr=0.3,0.1

Type RM Length L Ch R = 1 ,6293    ,228.2,234.1,233
XS GIS Cut Line= 2
2164766.37874355485916.0924654252164767.86120661486091.023105594
#Sta/Elev= 30
       0 2960.15     1.1 2959.29     5.1 2955.02     9.1 2951.14    17.1 2945.07
    21.1 2942.82    33.1 2937.07    37.1 2935.69    49.1 2934.04   55.272932.542
    57.1 2932.02    61.1 2931.47    65.1 2931.33    73.1 2931.51    77.1  2931.8
    81.1 2932.49    85.1 2933.52    89.1 2935.01    93.1 2935.83   105.1 2936.86
   117.1 2939.19   125.1 2939.03   129.1 2939.39   137.1 2941.07   145.7 2944.22
   153.1 2947.87   161.1 2951.38   169.1 2955.63   173.1 2956.91   174.9 2957.13
#Mann= 3 ,-1,0
       0      .1       0   55.27    .045       0    81.1      .1       0
Bank Sta=55.27,81.1
XS Rating Curve= 0 ,0
Exp/Cntr(USF)=0,0
Exp/Cntr=0.3,0.1

Type RM Length L Ch R = 1 ,6059    ,132.2,157,173.4
XS GIS Cut Line= 3
2164618.87366985485927.952169843 2164569.2111576486042.101824869
2164562.54007386486167.369952787
#Sta/Elev= 30
       0  2962.5     5.7 2960.73    12.1 2957.49    18.8 2953.28    30.3 2944.91
    36.4 2941.37    45.5 2934.84    49.3 2932.64    53.7 2931.07    66.8 2929.38
    75.5 2927.14    79.9 2926.77    92.9 2927.36   119.1 2925.12   131.6  2926.1
   135.6 2926.02   147.4 2923.37   155.6 2922.18   171.6 2921.39   175.6 2922.14
   177.4  2923.4   179.6 2924.96   183.6 2928.66   187.7 2933.17   195.7 2945.14
   211.7 2960.24   215.7 2963.25   223.7 2968.37   235.7 2974.15   249.9  2982.9
#Mann= 3 ,-1,0
       0      .1       0   147.4    .045       0   177.4      .1       0
#XS Ineff= 2 , 0
          132.96 2935.59
Permanent Ineff=
       F       F
Bank Sta=147.4,177.4
XS Rating Curve= 0 ,0
Exp/Cntr(USF)=0,0
Exp/Cntr=0.3,0.1

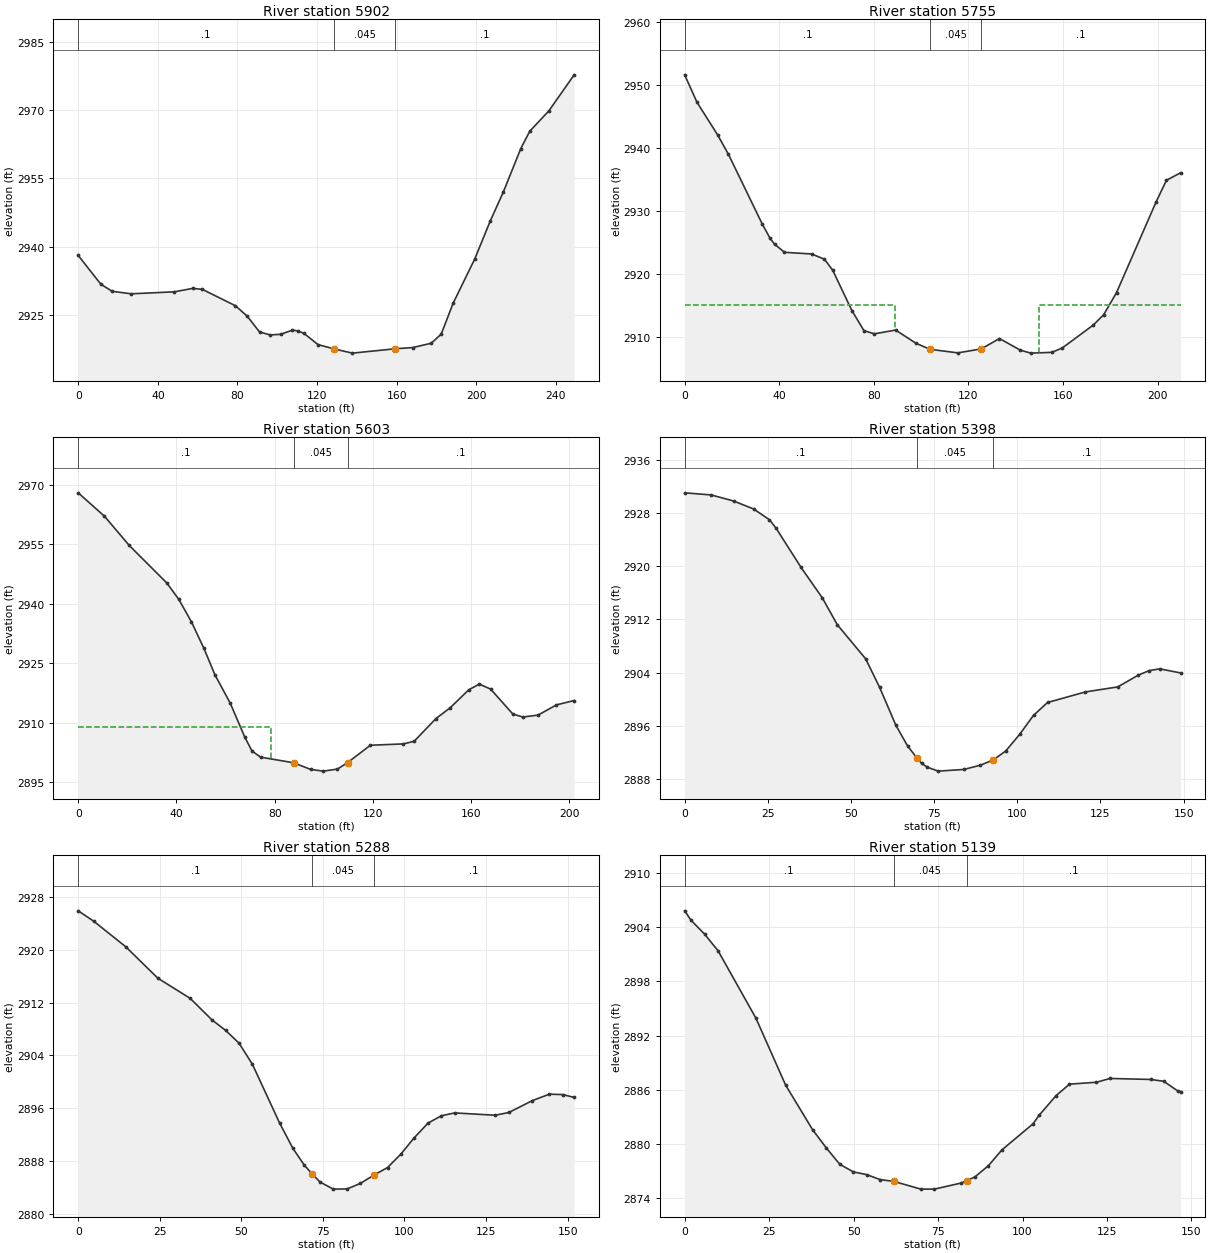
Type RM Length L Ch R = 1 ,5902    ,139.5,146.5,150.1
XS GIS Cut Line= 3
2164542.52682266485915.3512338992164467.99524189  485994.0181538
2164354.22316265486076.959928751
#Sta/Elev= 30
       0  2938.1    11.4 2931.78    17.1 2930.23    26.7 2929.69    48.2 2930.12
    57.6 2930.88    62.4 2930.66      79 2927.07      85 2924.75    91.1 2921.32
    96.5 2920.67   101.7  2920.8   107.6 2921.72   110.5 2921.54   113.4 2921.02
   120.5 2918.55  128.62  2917.6   137.8 2916.68   159.2 2917.63   168.1  2917.9
   177.4 2918.85   182.4 2920.85   188.4 2927.63   199.3 2937.38   207.1 2945.71
   213.6    2952   222.4 2961.55   226.9 2965.35   236.5 2969.81   249.2 2977.71
#Mann= 3 ,-1,0
       0      .1       0  128.62    .045       0   159.2      .1       0
Bank Sta=128.62,159.2
XS Rating Curve= 0 ,0
Exp/Cntr(USF)=0,0
Exp/Cntr=0.3,0.1

Type RM Length L Ch R = 1 ,5755    ,162.7,152.6,136.9
XS GIS Cut Line= 2
2164492.92086745485831.4016301172164302.66689312485919.684949141
#Sta/Elev= 30
       0 2951.57     5.2 2947.22    13.9 2942.06    18.5 2938.97    32.7 2927.99
    36.1 2925.64      38 2924.71    42.2 2923.43    53.7 2923.16    59.1 2922.33
    62.6 2920.58    70.7 2914.19    75.8    2911    80.2  2910.5    89.2  2911.1
    97.8    2909103.80042908.043   115.5 2907.48   125.4 2908.11   133.1 2909.75
   141.9 2907.92   146.3 2907.44   155.2 2907.56   159.6 2908.24   172.8  2911.9
   177.2 2913.55   182.6 2917.04   199.3 2931.39   203.7 2934.85   209.7 2936.04
#Mann= 3 ,-1,0
       0      .1       0103.8004    .045       0   125.4      .1       0
#XS Ineff= 2 , 0
       0      89    2915     150       0    2915
Permanent Ineff=
       F       F
Bank Sta=103.8004,125.4
XS Rating Curve= 0 ,0
Exp/Cntr(USF)=0,0
Exp/Cntr=0.3,0.1

Type RM Length L Ch R = 1 ,5603    ,205.7,204.3,201.3
XS GIS Cut Line= 3
2164364.63125638485687.0519238482164318.67490176485722.631037103
2164254.92899052485851.605322651
#Sta/Elev= 30
       0 2967.92    10.7 2962.02    20.8 2954.65    36.1  2945.2      41 2941.05
    46.1 2935.43    51.2 2928.73    55.7 2922.05    61.9 2914.95    67.9 2906.29
    70.8 2902.85    74.3 2901.32    87.7 2899.91    94.7 2898.22    99.9  2897.8
   105.6 2898.32   109.7 2899.94     119 2904.32   132.4 2904.66   136.8  2905.3
   145.7 2911.04   151.5 2913.76   159.1  2918.3   163.4 2919.72     168 2918.46
     177  2912.2   181.1 2911.43   187.3 2911.92   194.8 2914.49     202 2915.59
#Mann= 3 ,-1,0
       0      .1       0    87.7    .045       0   109.7      .1       0
#XS Ineff= 2 , 0
           78.34 2908.97
Permanent Ineff=
       F       F
Bank Sta=87.7,109.7
XS Rating Curve= 0 ,0
Exp/Cntr(USF)=0,0
Exp/Cntr=0.3,0.1

Type RM Length L Ch R = 1 ,5398    ,111.3,110.7,109.3
XS GIS Cut Line= 2
2164140.77933549485645.5429583842164094.08174934485787.118179877
#Sta/Elev= 30
       0 2931.04       8 2930.72    14.7 2929.81    20.7 2928.62    25.5 2926.99
    27.5  2925.7      35 2919.82    41.4 2915.23    45.9  2911.2    54.4 2906.09
    58.6  2901.8    63.5 2896.09      67    2893    69.9 2891.12    71.2 2890.38
      73 2889.78    76.2  2889.2    83.9 2889.45    88.9 2890.09    92.8 2890.89
    96.5 2892.22   100.7 2894.72   104.9  2897.6   109.1 2899.52   120.5 2901.11
   130.2 2901.86   136.4 2903.64   139.6  2904.3   142.8 2904.58   149.1 2903.96
#Mann= 3 ,-1,0
       0      .1       0    69.9    .045       0    92.8      .1       0
Bank Sta=69.9,92.8
XS Rating Curve= 0 ,0
Exp/Cntr(USF)=0,0
Exp/Cntr=0.3,0.1

Type RM Length L Ch R = 1 ,5288    ,153.5,148.9,141.5
XS GIS Cut Line= 2
2164030.26009998485613.4680579942163991.93555839485760.606923034
#Sta/Elev= 30
       0 2925.92     4.8 2924.33    14.6 2920.46    24.4 2915.71    34.3 2912.66
      41 2909.39    45.2 2907.79    49.3 2905.86    53.4 2902.65    61.7 2893.78
    65.8 2889.92    69.3 2887.37    71.8 2885.99    74.1 2884.82    78.2 2883.74
    82.4 2883.77    86.5 2884.61    90.6 2885.86    94.8 2887.01    98.9 2889.05
   102.9 2891.48   107.2 2893.74   111.3 2894.86   115.4 2895.29   127.8 2894.94
     132 2895.36   139.2 2897.16   144.4 2898.13   148.5 2898.07     152 2897.64
#Mann= 3 ,-1,0
       0      .1       0    71.8    .045       0    90.6      .1       0
Bank Sta=71.8,90.6
XS Rating Curve= 0 ,0
Exp/Cntr(USF)=0,0
Exp/Cntr=0.3,0.1

Type RM Length L Ch R = 1 ,5139    ,126.5,126.7,127.2
XS GIS Cut Line= 2
2163872.45352303485583.2795101882163876.15968066485730.043352364
#Sta/Elev= 30
       0 2905.81     1.9 2904.76     5.9 2903.23     9.9 2901.38    21.1 2893.93
    29.9 2886.52    37.9 2881.58    41.9  2879.6    45.9 2877.78    49.9 2876.94
    53.9 2876.63    57.9 2876.08    61.9 2875.89    69.9 2875.03    73.9 2875.03
    81.9 2875.71    83.5 2875.98    85.9 2876.38    89.9 2877.62    93.9 2879.37
   103.1 2882.25   104.9 2883.19   109.9 2885.36   113.9 2886.64   121.9 2886.85
   125.9 2887.27   137.9 2887.16   141.8 2886.96   145.9  2885.9   146.8 2885.82
#Mann= 3 ,-1,0
       0      .1       0    61.9    .045       0    83.5      .1       0
Bank Sta=61.9,83.5
XS Rating Curve= 0 ,0
Exp/Cntr(USF)=0,0
Exp/Cntr=0.3,0.1

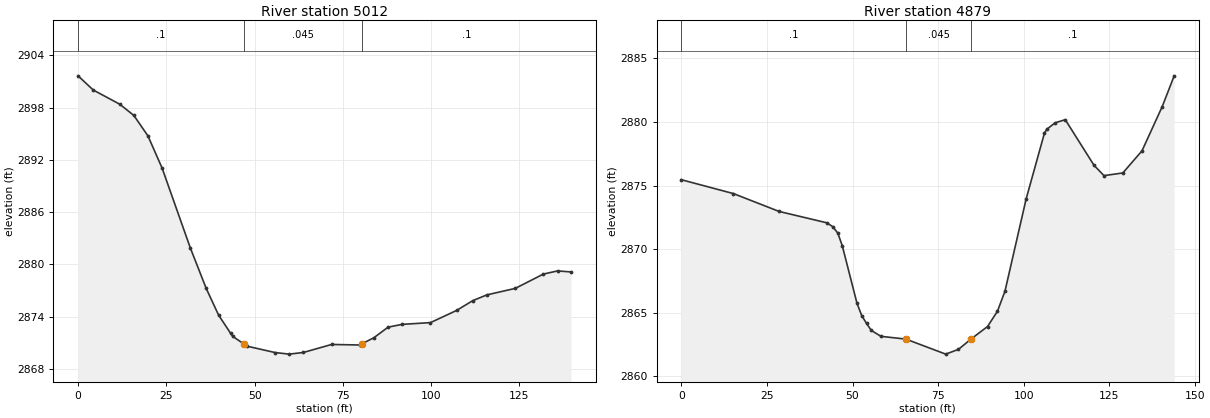
Type RM Length L Ch R = 1 ,5012    ,151,133.1,117.5
XS GIS Cut Line= 2
2163747.61660574485585.4090186142163747.61660574485725.019848699
#Sta/Elev= 30
       0 2901.66     4.3 2900.03    11.8  2898.4    15.8 2897.11    19.8 2894.75
    23.8 2891.06    31.8 2881.88    36.3 2877.23    39.8 2874.17    43.2 2872.08
    43.8 2871.73   46.88 2870.88    47.8 2870.61    55.8 2869.87    59.8 2869.69
    63.8 2869.88    71.8  2870.8    79.8 2870.74    80.3 2870.86    83.8 2871.58
    87.8 2872.79    91.8 2873.11    99.8 2873.31   107.2 2874.71   111.8 2875.84
   115.8  2876.5   123.8 2877.24   131.8 2878.89   135.8 2879.25   139.6 2879.13
#Mann= 3 ,-1,0
       0      .1       0   46.88    .045       0    80.3      .1       0
Bank Sta=46.88,80.3
XS Rating Curve= 0 ,0
Exp/Cntr(USF)=0,0
Exp/Cntr=0.3,0.1

Type RM Length L Ch R = 1 ,4879    ,68.8,115.4,147.1
XS GIS Cut Line= 3
2163603.38647904 485642.578032282163614.50495193485681.122071639
2163686.40440997485755.986455779
#Sta/Elev= 30
       0 2875.46    15.2 2874.37    28.6 2872.96    42.5 2872.07    44.2 2871.77
    45.7 2871.26      47 2870.27    51.3 2865.74    52.7 2864.76    54.1 2864.15
    55.5  2863.6    58.3 2863.14    65.6 2862.92    77.2 2861.74    80.9 2862.11
    84.6 2862.93    89.4 2863.91    92.3 2865.11    94.5 2866.69   100.7 2873.97
     106  2879.1   106.7 2879.43   109.2 2879.94   112.1 2880.18   120.5 2876.59
   123.4 2875.78   128.9 2875.99   134.5 2877.73   140.4 2881.21   143.9 2883.63
#Mann= 3 ,-1,0
       0      .1       0    65.6    .045       0    84.6      .1       0
Bank Sta=65.6,84.6
XS Rating Curve= 0 ,0
Exp/Cntr(USF)=0,0
Exp/Cntr=0.3,0.1