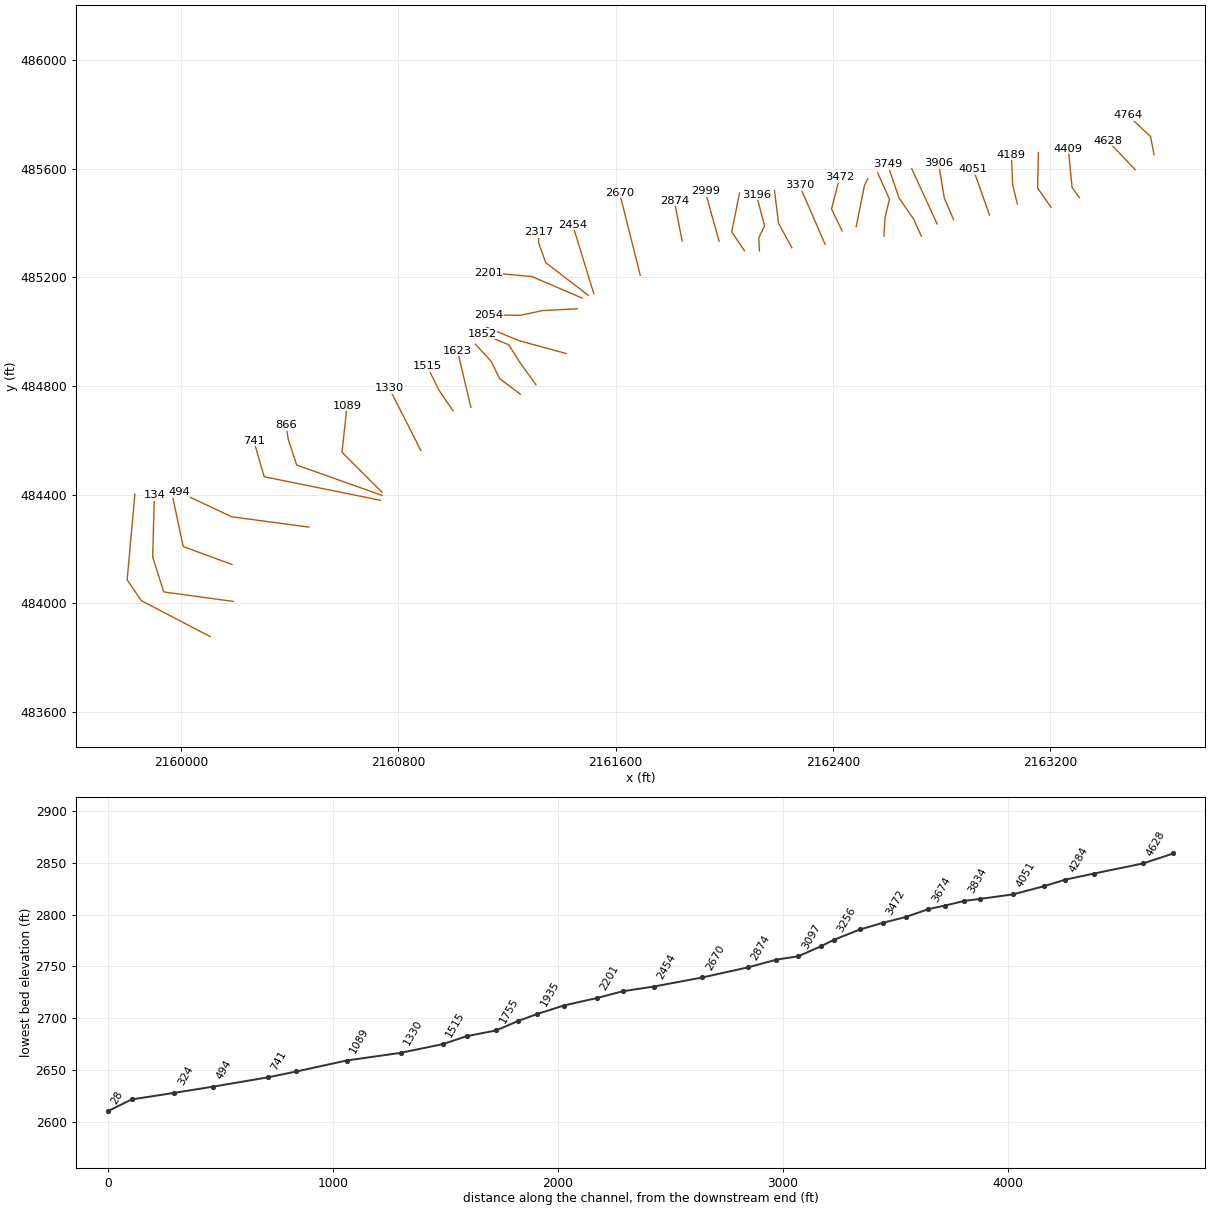
HEC-RAS study BEECHYRN.prj: BEECHYRN

--- BEECHYRN.g01 (geometry) --- (continued)

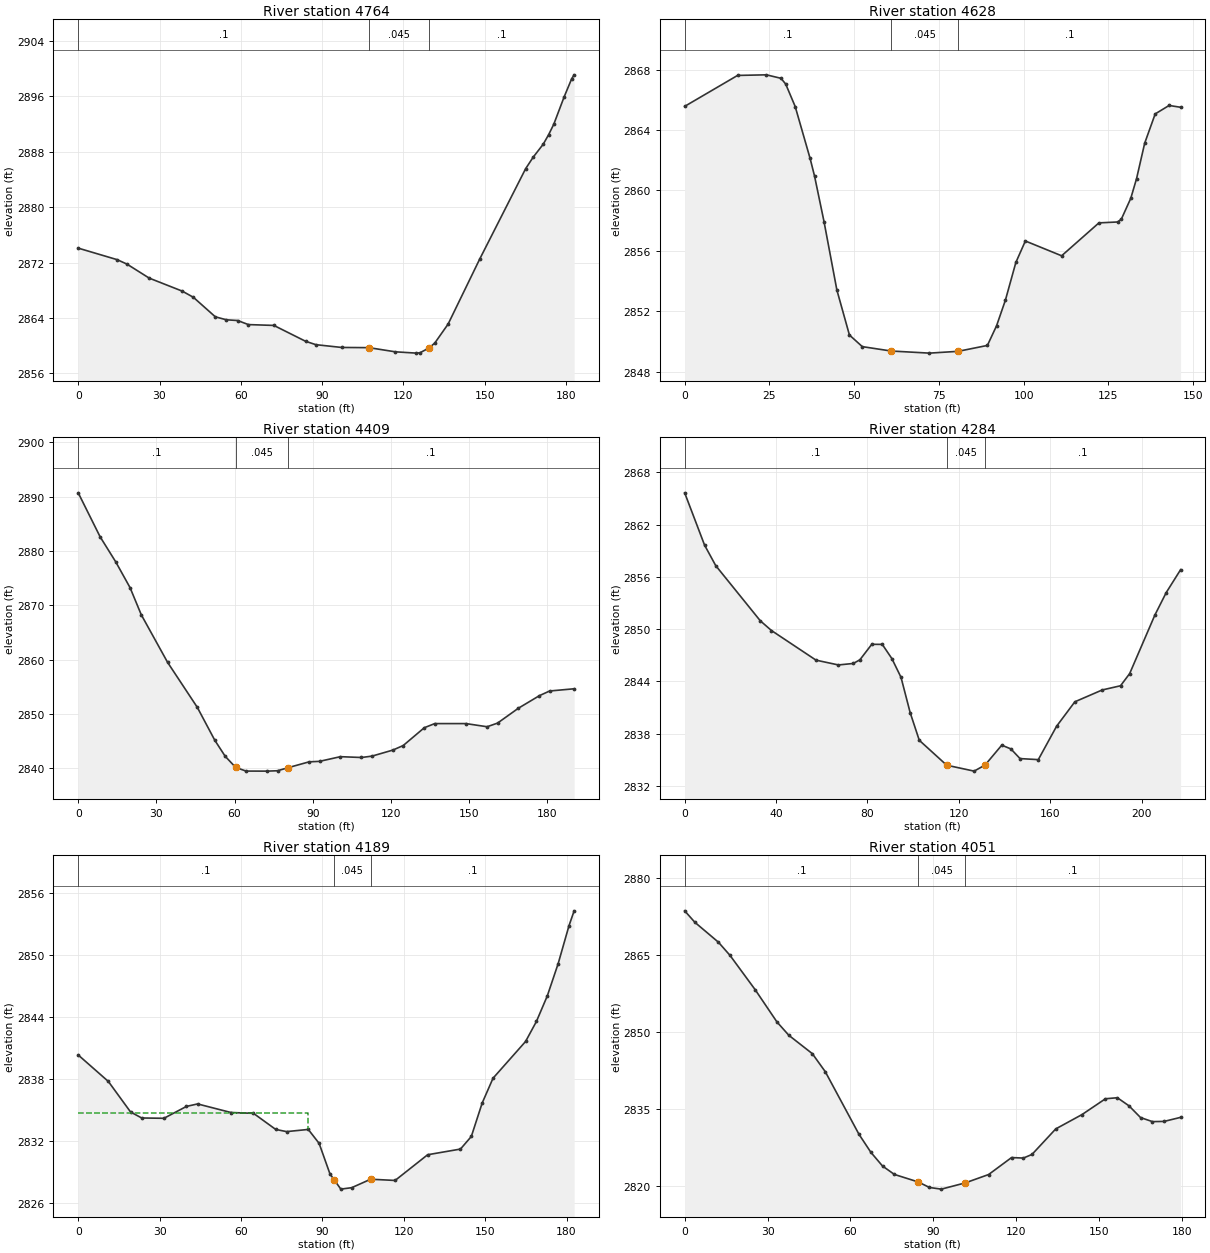
Type RM Length L Ch R = 1 ,4764    ,135.5,135.3,128.4
XS GIS Cut Line= 3
2163583.30625231485651.4748186772163570.42868332485718.438177423
2163486.72448489 485796.99134826
#Sta/Elev= 30
       0 2874.08    14.4 2872.41      18 2871.77    26.2 2869.75    38.4 2867.87
    42.5 2866.98    50.6 2864.16    54.7 2863.73    58.8 2863.63    62.8 2863.04
    72.2 2862.92    83.9 2860.63    87.7 2860.14    97.2 2859.74   107.3 2859.71
     117 2859.11   124.8 2858.92   126.1 2858.97  129.51 2859.68   131.6 2860.39
   136.5 2863.12   148.1 2872.46   165.1 2885.55   167.9 2887.22   171.6 2889.09
   173.6 2890.47   175.5 2891.98   179.3 2895.91   182.1 2898.54     183  2899.1
#Mann= 3 ,-1,0
       0      .1       0   107.3    .045       0  129.51      .1       0
Bank Sta=107.3,129.51
XS Rating Curve= 0 ,0
Exp/Cntr(USF)=0,0
Exp/Cntr=0.3,0.1

Type RM Length L Ch R = 1 ,4628    ,231.6,219.2,204.7
XS GIS Cut Line= 2
2163513.69746438485596.6216776592163412.88997682485702.617785897
#Sta/Elev= 30
       0 2865.57    15.6 2867.62    24.1 2867.66    28.4 2867.43    29.8 2867.05
    32.6 2865.56      37 2862.12    38.3 2860.96    41.1 2857.94    44.9  2853.4
    48.6 2850.42    52.4 2849.65    60.9 2849.36    72.2 2849.22    80.7 2849.34
    89.3 2849.73      92 2851.03    94.6 2852.72    97.7 2855.23   100.5 2856.65
   111.2 2855.67   122.2 2857.85   127.7 2857.91   128.8 2858.09   131.6 2859.48
   133.3 2860.78   135.7 2863.13   138.8 2865.07   142.9 2865.63   146.3 2865.51
#Mann= 3 ,-1,0
       0      .1       0    60.9    .045       0    80.7      .1       0
Bank Sta=60.9,80.7
XS Rating Curve= 0 ,0
Exp/Cntr(USF)=0,0
Exp/Cntr=0.3,0.1

Type RM Length L Ch R = 1 ,4409    ,127.2,125.2,122.3
XS GIS Cut Line= 3
  2163308.333786485493.5690618732163281.45914455 485530.51513051
2163267.31417298485674.407355228
#Sta/Elev= 30
       0 2890.69     8.4  2882.6    14.4 2877.98    19.9 2873.23    24.2 2868.24
    34.3 2859.48    45.7  2851.2    52.4 2845.15    56.4 2842.19    60.4 2840.15
    64.4 2839.47    72.5 2839.46    76.5 2839.53    80.5 2840.09    88.6 2841.17
    92.6 2841.26   100.6 2842.12   108.7 2841.97   112.7 2842.22   120.7 2843.33
   124.7 2844.17   132.8 2847.45   136.8 2848.21   148.8 2848.21   156.9 2847.63
   160.9  2848.3   168.9 2851.04     177 2853.36   180.9 2854.21   190.3 2854.62
#Mann= 3 ,-1,0
       0      .1       0    60.4    .045       0    80.5      .1       0
Bank Sta=60.4,80.5
XS Rating Curve= 0 ,0
Exp/Cntr(USF)=0,0
Exp/Cntr=0.3,0.1

Type RM Length L Ch R = 1 ,4284    ,94.1,95.1,95.7
XS GIS Cut Line= 3
2163203.83347062 485458.02475589 2163154.3141944485528.912229282
2163157.38947843485659.484020007
#Sta/Elev= 30
       0 2865.64     8.7 2859.64    13.6 2857.28    33.1 2850.95      38 2849.83
    57.5 2846.43    67.3 2845.88    73.8 2846.05    76.7 2846.47    81.9 2848.25
    86.5 2848.24    90.7 2846.61    94.7 2844.46    98.7 2840.41   102.7 2837.23
   114.7 2834.37   126.7 2833.69   131.5 2834.39   138.8 2836.67   142.8 2836.24
   146.8 2835.13   154.8 2835.01   162.8 2838.84   170.8 2841.65   182.8 2843.01
   190.8 2843.49   194.8 2844.89   205.8 2851.59   210.8 2854.19   217.1 2856.82
#Mann= 3 ,-1,0
       0      .1       0   114.7    .045       0   131.5      .1       0
Bank Sta=114.7,131.5
XS Rating Curve= 0 ,0
Exp/Cntr(USF)=0,0
Exp/Cntr=0.3,0.1

Type RM Length L Ch R = 1 ,4189    ,134,138,139.6
XS GIS Cut Line= 3
2163079.67459514485470.4353938382163062.56542479485540.925175695
2163057.77485709485651.108232771
#Sta/Elev= 30
       0 2840.32    11.1 2837.76    19.3  2834.8    23.4 2834.22    31.6 2834.19
    39.9 2835.34      44 2835.58    56.3 2834.75    64.6 2834.67    72.8 2833.11
    76.8  2832.9    84.8 2833.11    88.8 2831.76    92.8  2828.8    94.3 2828.25
    96.8 2827.33   100.8 2827.47   107.8 2828.29   116.8 2828.17   128.8 2830.66
   140.9 2831.21   144.9 2832.43   148.9 2835.67   152.9 2838.07   164.9 2841.63
   168.9 2843.57   172.9 2846.04   176.9 2849.16   180.9 2852.84   182.8 2854.28
#Mann= 3 ,-1,0
       0      .1       0    94.3    .045       0   107.8      .1       0
#XS Ineff= 2 , 0
           84.73 2834.66
Permanent Ineff=
       F       F
Bank Sta=94.3,107.8
XS Rating Curve= 0 ,0
Exp/Cntr(USF)=0,0
Exp/Cntr=0.3,0.1

Type RM Length L Ch R = 1 ,4051    ,144.9,145.1,142.1
XS GIS Cut Line= 2
 2162977.2416054485429.7013144312162917.00608583485598.845372237
#Sta/Elev= 30
       0 2873.64     3.7  2871.4    12.2 2867.54    16.4 2864.97    25.5  2858.3
    33.4 2852.01    37.7 2849.41    46.2 2845.84    50.9 2842.32    63.1 2830.13
    67.4 2826.63    71.6 2823.97    75.9 2822.3384.581642820.856    88.6 2819.79
    92.9 2819.47101.5813 2820.69     110 2822.31   118.3 2825.61   122.6 2825.52
   125.7 2826.22   134.3 2831.19   143.8 2833.98   152.3 2837.06   156.6 2837.26
   160.8 2835.69     165  2833.4   169.3 2832.61   173.5 2832.65   179.5 2833.44
#Mann= 3 ,-1,0
       0      .1       084.58164    .045       0101.5813      .1       0
Bank Sta=84.58164,101.5813
XS Rating Curve= 0 ,0
Exp/Cntr(USF)=0,0
Exp/Cntr=0.3,0.1

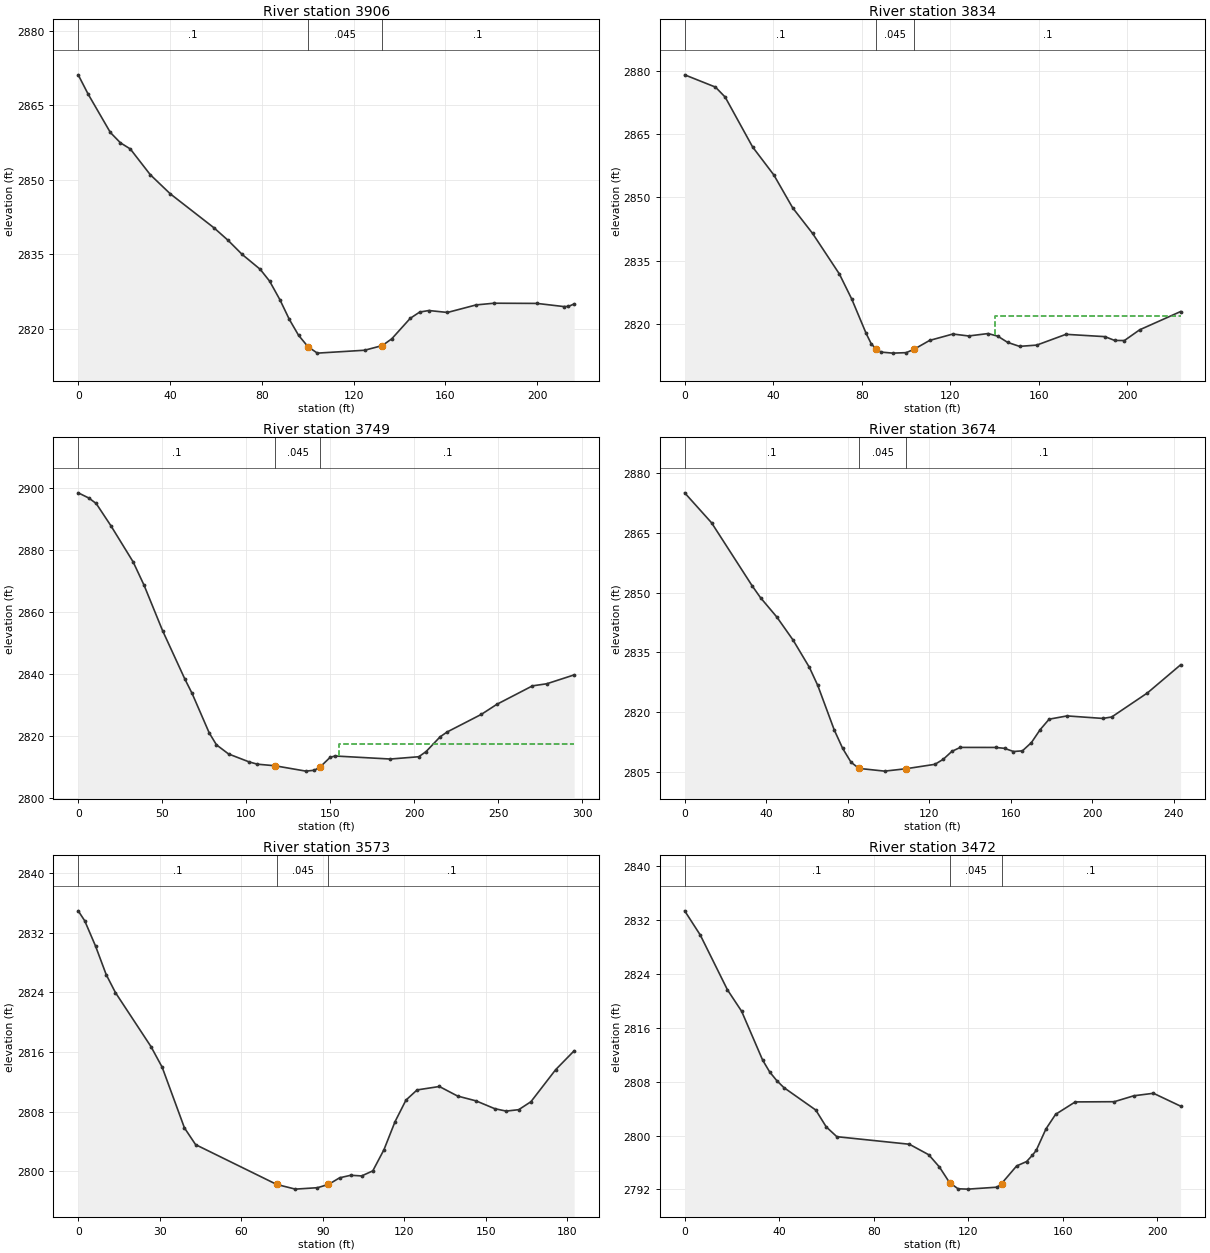
Type RM Length L Ch R = 1 ,3906    ,66.9,71.5,78.1
XS GIS Cut Line= 3
2162844.93677789485412.2642146362162810.71843718485492.335131891
2162789.50306594485619.627359321
#Sta/Elev= 30
       0 2871.09     4.3 2867.23      14  2859.5    18.4 2857.41    22.7 2856.18
    31.4    2851    40.1 2847.16    59.2  2840.3    65.3  2837.8    71.4 2834.98
    79.3 2831.97    83.4 2829.59    87.9 2825.84      92 2821.89      96 2818.71
   100.1 2816.41   104.2 2815.11   124.8 2815.69   132.5 2816.63   136.6 2817.98
   144.7 2822.12   148.8 2823.37   152.8 2823.68   160.9 2823.29   173.4 2824.81
   181.2 2825.15   199.9 2825.11   211.5 2824.48   213.6  2824.5   216.1 2825.01
#Mann= 3 ,-1,0
       0      .1       0   100.1    .045       0   132.5      .1       0
Bank Sta=100.1,132.5
XS Rating Curve= 0 ,0
Exp/Cntr(USF)=0,0
Exp/Cntr=0.3,0.1

Type RM Length L Ch R = 1 ,3834    ,80.9,85.4,86.7
XS GIS Cut Line= 2
2162784.28836012485396.5908970642162690.72485456485600.229115043
#Sta/Elev= 30
       0    2879    13.9  2876.1    18.3 2873.73    30.7 2861.93    40.3  2855.3
    48.8 2847.53    57.8 2841.47    69.9 2831.88    75.5 2825.93      82 2817.81
    84.3 2815.36    86.5 2814.11    88.7  2813.4      94 2813.15   100.1 2813.26
  103.74 2814.09   110.7 2816.16   121.2 2817.67   128.3 2817.21   137.1 2817.78
   141.5 2817.16   145.9  2815.7   151.3 2814.75   159.1 2815.05   172.3  2817.6
   189.9 2817.05   194.3 2816.15   198.7 2816.13   205.6 2818.67   224.1 2822.99
#Mann= 3 ,-1,0
       0      .1       0    86.5    .045       0  103.74      .1       0
#XS Ineff= 2 , 0
                             140            2822
Permanent Ineff=
       F       F
Bank Sta=86.5,103.74
XS Rating Curve= 0 ,0
Exp/Cntr(USF)=0,0
Exp/Cntr=0.3,0.1

Type RM Length L Ch R = 1 ,3749    ,89.2,74.4,60.6
XS GIS Cut Line= 4
2162726.27728437 485351.410933422162698.34842675485413.304406596
  2162644.262637485491.857577433 2162601.4602735 485616.61755793
#Sta/Elev= 30
       0  2898.4     6.3 2896.73    10.7 2894.96    19.5 2887.75    32.7 2876.13
    39.2 2868.61    50.2    2854    63.4 2838.46    67.8 2833.72      78 2820.99
    82.3 2817.16    89.5 2814.22   101.7 2811.67   106.6 2810.93117.11142810.421
   135.5 2808.69   140.6 2808.97   144.2 2810.13   149.9 2813.11   152.8 2813.57
   185.8 2812.59   202.7 2813.33     207 2814.96   215.4 2819.74   219.6 2821.31
     240    2827   249.2 2830.23   270.4 2836.18   278.9 2836.85   295.2 2839.71
#Mann= 3 ,-1,0
       0      .1       0117.1114    .045       0   144.2      .1       0
#XS Ineff= 2 , 0
                          155.32         2817.36
Permanent Ineff=
       F       F
Bank Sta=117.1114,144.2
XS Rating Curve= 0 ,0
Exp/Cntr(USF)=0,0
Exp/Cntr=0.3,0.1

Type RM Length L Ch R = 1 ,3674    ,99.3,101,100.7
XS GIS Cut Line= 4
2162588.29922259485352.0399349922162592.40542347485420.476616406
2162608.83022701485487.5445641922162565.71511772485584.040284986
#Sta/Elev= 30
       0 2875.01    13.2 2867.49    33.2 2851.61    37.2 2848.71    45.2 2843.86
    53.2 2838.06    61.2 2831.21    65.3 2826.68    73.4  2815.5    77.5 2810.91
    81.6 2807.44    85.5 2805.88    98.1  2805.2   108.6  2805.8   122.8 2806.91
   126.9 2808.19   131.1 2810.16   135.2 2811.15   152.5 2811.14   156.9 2810.92
   161.3 2810.12   165.7 2810.29   170.1 2812.36   174.4 2815.61   178.8 2818.23
   187.6 2819.05   205.1 2818.42   209.5 2818.78     227 2824.81   243.3 2831.87
#Mann= 3 ,-1,0
       0      .1       0    85.5    .045       0   108.6      .1       0
Bank Sta=85.5,108.6
XS Rating Curve= 0 ,0
Exp/Cntr(USF)=0,0
Exp/Cntr=0.3,0.1

Type RM Length L Ch R = 1 ,3573    ,101.6,101.2,99.9
XS GIS Cut Line= 3
2162486.35056915485386.8531557612162516.74106172485539.546850146
2162529.34199766485563.266258983
#Sta/Elev= 30
       0 2834.95     2.4 2833.61     6.4  2830.2    10.3 2826.39    13.7 2823.98
    26.8 2816.72    30.9 2813.96    39.1 2805.82    43.2 2803.58   73.03 2798.24
    79.9 2797.61      88  2797.8    92.1 2798.24    96.2 2799.13   100.3 2799.47
   104.3 2799.38   108.4 2800.06   112.5 2802.89   116.6 2806.67   120.6 2809.55
   124.7 2810.92   132.9 2811.38   139.6  2810.1   146.4 2809.45   153.3  2808.4
   157.5 2808.08   162.1 2808.27   166.6 2809.34   175.7 2813.64   182.5 2816.17
#Mann= 3 ,-1,0
       0      .1       0   73.03    .045       0    92.1      .1       0
Bank Sta=73.03,92.1
XS Rating Curve= 0 ,0
Exp/Cntr(USF)=0,0
Exp/Cntr=0.3,0.1

Type RM Length L Ch R = 1 ,3472    ,90.2,101.7,111.7
XS GIS Cut Line= 3
 2162434.3166894485371.202205788  2162395.307781485451.957489856
2162425.41992082 485568.29984826
#Sta/Elev= 30
       0 2833.34     6.6 2829.75    18.1 2821.62    24.1 2818.44      33 2811.19
      36 2809.42      39 2808.14      42 2807.11    55.5 2803.78    59.9 2801.29
    64.4 2799.83    95.1 2798.71   103.3 2797.15   107.8 2795.34   112.12793.023
   115.7  2792.1   119.9 2792.05   132.3 2792.34   134.1 2792.87   140.5 2795.49
   144.7 2796.14   147.2 2797.09   148.8 2797.81   152.9 2800.98     157 2803.15
   165.3 2804.99   181.8 2805.02   190.1  2805.9   198.4 2806.27   209.9 2804.36
#Mann= 3 ,-1,0
       0      .1       0   112.1    .045       0   134.1      .1       0
Bank Sta=112.1,134.1
XS Rating Curve= 0 ,0
Exp/Cntr(USF)=0,0
Exp/Cntr=0.3,0.1

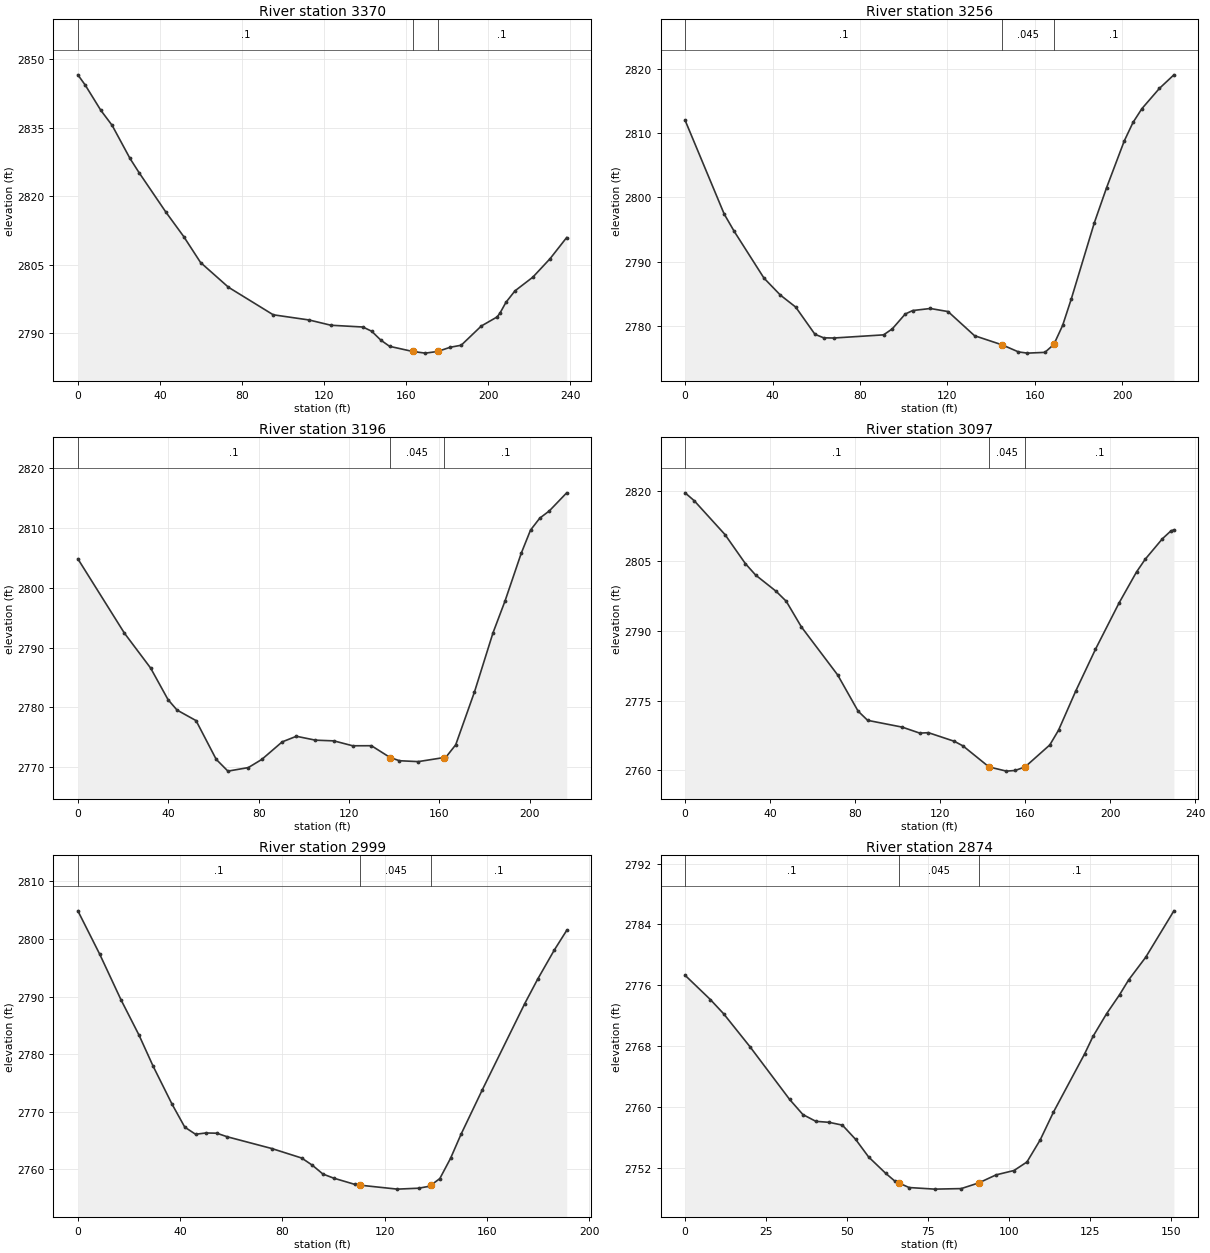
Type RM Length L Ch R = 1 ,3370    ,119.1,114.7,109.6
XS GIS Cut Line= 2
2162371.60472975485321.8783754272162276.58204725485540.288081672
#Sta/Elev= 30
       0 2846.59     3.6 2844.34    11.2 2838.81    16.7 2835.52    25.4 2828.28
    29.8 2825.18    42.9 2816.51    51.6 2811.15    59.8 2805.47    73.4 2800.05
    95.2 2794.02   112.7 2792.88   123.3 2791.73   138.9 2791.34   143.2 2790.41
   147.6 2788.48   151.9 2787.11   163.2 2785.98   169.3 2785.62   175.3 2785.98
   181.4  2786.9   186.8 2787.35   196.6 2791.56   204.3 2793.55   205.7 2794.39
   208.6 2796.75     213 2799.26   221.7 2802.26   230.1 2806.31   238.2 2810.95
#Mann= 3 ,-1,0
       0      .1       0   163.2    .045       0   175.3      .1       0
Bank Sta=163.2,175.3
XS Rating Curve= 0 ,0
Exp/Cntr(USF)=0,0
Exp/Cntr=0.3,0.1

Type RM Length L Ch R = 1 ,3256    ,57.6,59.7,62.1
XS GIS Cut Line= 3
2162248.98288775485309.4050711672162200.27763952485399.203642952
2162185.20716906485519.709804456
#Sta/Elev= 30
       0 2811.97    17.9 2797.38    22.5 2794.68    36.1 2787.42    43.6 2784.78
    50.6 2782.92    59.4 2778.69    63.4 2778.14      68 2778.11    90.8  2778.6
    94.8 2779.54   100.7 2781.84   104.1 2782.38   112.2  2782.7   120.3 2782.22
   132.4 2778.47145.09852777.037   152.5 2775.95   156.6 2775.76   164.6 2775.88
168.69672777.122   172.7 2780.07   176.7 2784.23   187.2 2796.03   192.8 2801.48
   200.9 2808.76   204.9 2811.63     209 2813.79     217 2816.93   223.6 2819.03
#Mann= 3 ,-1,0
       0      .1       0145.0985    .045       0168.6967      .1       0
Bank Sta=145.0985,168.6967
XS Rating Curve= 0 ,0
Exp/Cntr(USF)=0,0
Exp/Cntr=0.3,0.1

Type RM Length L Ch R = 1 ,3196    ,104.5,98.9,90.5
XS GIS Cut Line= 4
2162129.77345711 485297.290589862162127.72035667485345.880633664
2162148.93572791485389.6801097692162118.13922127485504.653734545
#Sta/Elev= 30
       0 2804.85    20.6 2792.42    32.2 2786.58    39.9  2781.3    43.9 2779.55
    52.3 2777.79    61.2 2771.32    66.4 2769.34    75.4 2769.93    81.4  2771.3
    90.4 2774.23    96.7 2775.17   105.1 2774.52   113.3  2774.4   121.6 2773.58
   129.9 2773.59   138.2 2771.61   142.3 2771.08   150.6 2770.93     1622771.611
     163 2771.74   167.2 2773.75   175.5 2782.59   183.7 2792.48     189 2797.78
   196.2 2805.79   200.3 2809.66   204.4 2811.66   208.6 2812.86   216.3 2815.89
#Mann= 3 ,-1,0
       0      .1       0   138.2    .045       0     162      .1       0
Bank Sta=138.2,162
XS Rating Curve= 0 ,0
Exp/Cntr(USF)=0,0
Exp/Cntr=0.3,0.1

Type RM Length L Ch R = 1 ,3097    ,85.5,97.5,107.7
XS GIS Cut Line= 3
2162074.71170086485297.6152783172162027.78445919485367.442967235
2162056.58310844485510.441277374
#Sta/Elev= 30
       0 2819.58     4.3 2817.89    18.8 2810.61    28.4 2804.37    33.2 2801.93
    42.8 2798.46    47.6 2796.31    54.7 2790.82    71.8 2780.49    81.4 2772.73
    85.9 2770.75   102.2 2769.29   110.4 2768.01   114.5  2768.1   126.7 2766.25
   130.8 2765.25     143 2760.75   151.2 2759.85   155.3 2759.99     1602760.765
   171.6 2765.47   175.7 2768.62   183.8 2777.03   193.1 2786.01   204.2 2795.95
   212.4 2802.59   216.5 2805.33   224.6 2809.73   228.6 2811.41     230 2811.64
#Mann= 3 ,-1,0
       0      .1       0     143    .045       0     160      .1       0
Bank Sta=143,160
XS Rating Curve= 0 ,0
Exp/Cntr(USF)=0,0
Exp/Cntr=0.3,0.1

Type RM Length L Ch R = 1 ,2999    ,127.5,125.9,124.5
XS GIS Cut Line= 2
2161981.26585844485332.8776641962161929.93834738  485516.9723372
#Sta/Elev= 30
       0 2804.88     8.6  2797.3    16.9  2789.4    23.9 2783.31    29.4 2777.93
    36.8 2771.33    41.8 2767.32      46 2766.09    50.1 2766.31    54.3 2766.27
    58.4 2765.65    75.8 2763.61    87.5 2761.96    91.7  2760.7    95.8 2759.18
     100 2758.47   108.3 2757.38  110.44 2757.24   124.9 2756.56   133.2 2756.72
   137.1 2757.03   138.1 2757.27   141.5 2758.39   145.7 2761.91   149.8 2766.09
   158.1 2773.79   174.7 2788.77   179.7 2792.97   186.2 2798.03   191.1 2801.48
#Mann= 3 ,-1,0
       0      .1       0  110.44    .045       0   138.1      .1       0
Bank Sta=110.44,138.1
XS Rating Curve= 0 ,0
Exp/Cntr(USF)=0,0
Exp/Cntr=0.3,0.1

Type RM Length L Ch R = 1 ,2874    ,200.6,203.3,203.2
XS GIS Cut Line= 2
2161845.18529904485333.4844858792161816.27726952485481.730791107
#Sta/Elev= 30
       0 2777.31     7.8 2774.12    11.9 2772.25    20.1 2767.88    32.3 2760.97
    36.4 2758.98    40.4 2758.09    44.5 2757.96    48.6 2757.59    52.7 2755.71
    56.7  2753.4      62 2751.24    64.9 2750.19   65.93    2750    69.2 2749.38
    77.1 2749.17    85.3 2749.24   90.72 2749.99    96.1 2751.05   101.6 2751.62
   105.6 2752.74   109.7 2755.65   113.8 2759.31   123.4 2766.95     126 2769.26
   130.2 2772.25   134.2 2774.74     137 2776.69   142.3 2779.69     151 2785.79
#Mann= 3 ,-1,0
       0      .1       0   65.93    .045       0   90.72      .1       0
Bank Sta=65.93,90.72
XS Rating Curve= 0 ,0
Exp/Cntr(USF)=0,0
Exp/Cntr=0.3,0.1

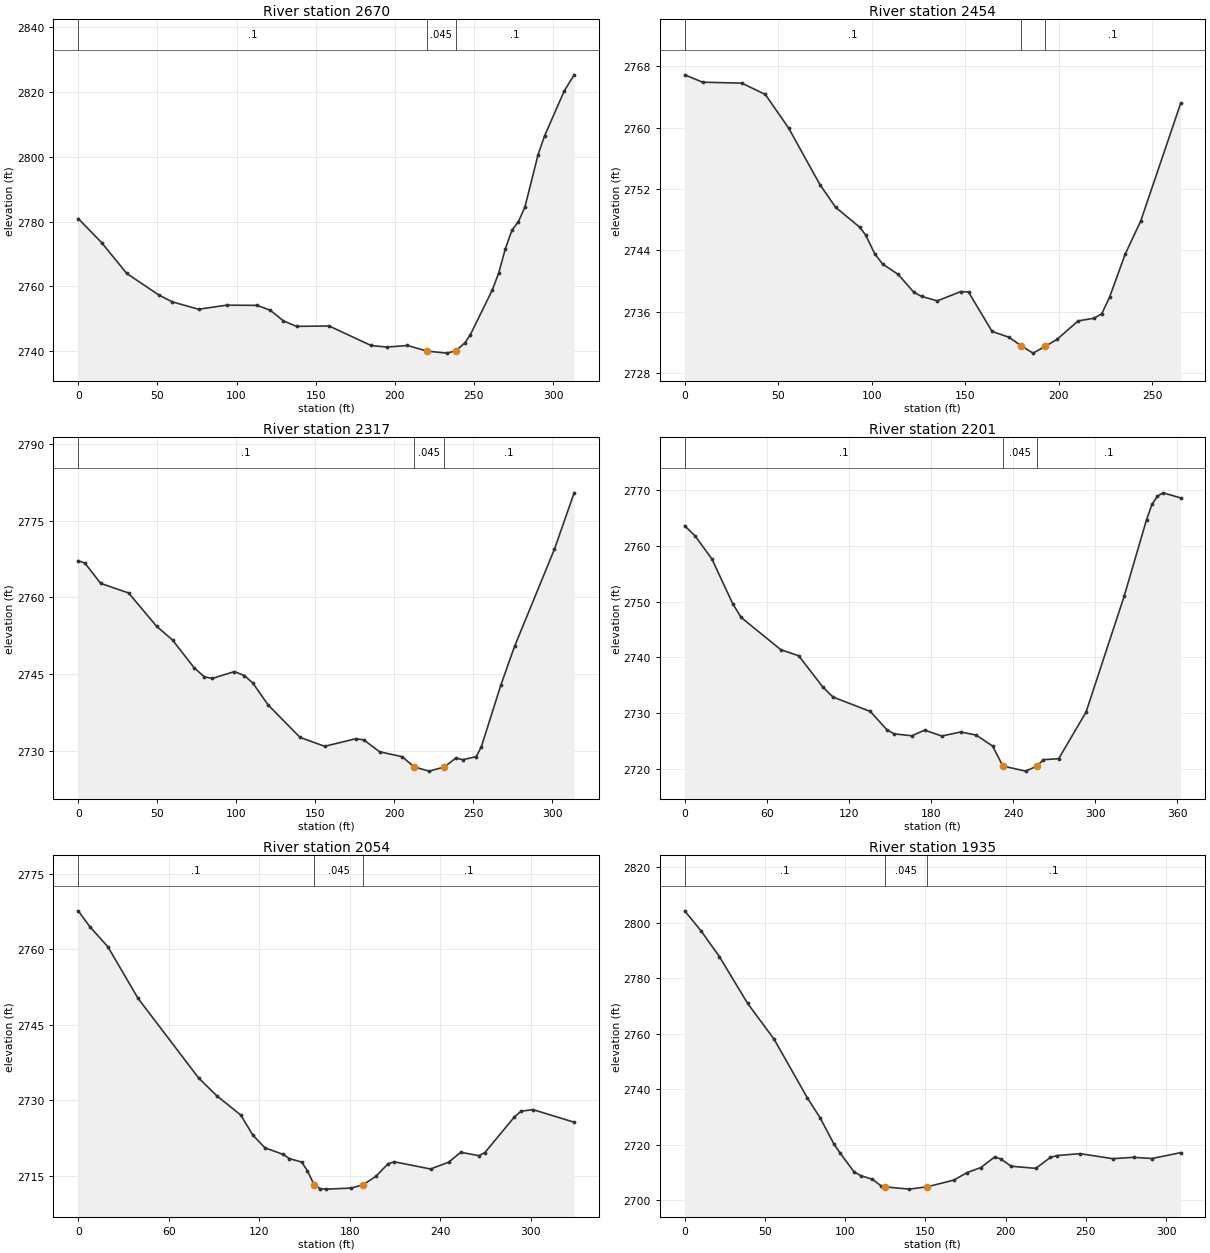
Type RM Length L Ch R = 1 ,2670    ,211.1,215.9,219.2
XS GIS Cut Line= 2
 2161691.0091416485207.4751264352161614.66229441485511.380052153
#Sta/Elev= 30
       0 2780.94      15 2773.39    30.6 2764.01    51.2 2757.24    59.5 2755.21
      76 2752.93    93.7 2754.19   113.1 2754.13   121.4  2752.6   129.6 2749.34
   137.9 2747.65   158.5 2747.76     185 2741.74   194.9 2741.25     208 2741.74
   220.3 2740.02   232.7 2739.38  238.36 2740.03   244.4 2742.63   247.7 2745.05
   261.6 2758.88   265.7 2764.22   269.8 2771.54     274 2777.33   278.1 2779.98
   282.2 2784.51   290.5 2800.64   294.6 2806.46   307.1  2820.4   313.3 2825.32
#Mann= 3 ,-1,0
       0      .1       0   220.3    .045       0  238.36      .1       0
Bank Sta=220.3,238.36
XS Rating Curve= 0 ,0
Exp/Cntr(USF)=0,0
Exp/Cntr=0.3,0.1

Type RM Length L Ch R = 1 ,2454    ,136.9,137.6,138.2
XS GIS Cut Line= 2
2161519.78465906485140.0230575572161441.95534882485393.524239497
#Sta/Elev= 30
       0 2766.87     9.6 2765.91    30.5 2765.79    43.1 2764.32    55.6 2759.93
    72.3 2752.58    80.7 2749.62    93.5 2747.04    96.7 2746.04   101.6 2743.58
   105.8 2742.23   114.2 2740.87   122.6 2738.53   126.7 2738.01   135.1 2737.43
   147.7 2738.64   151.8 2738.57   164.4 2733.44   173.5 2732.68   179.9 2731.58
   186.3 2730.62   192.7 2731.49   199.1 2732.41   210.4 2734.82   218.8 2735.16
     223 2735.74   227.2  2737.9   235.5 2743.48   243.9 2747.85   265.2 2763.14
#Mann= 3 ,-1,0
       0      .1       0   179.9    .045       0   192.7      .1       0
Bank Sta=179.9,192.7
XS Rating Curve= 0 ,0
Exp/Cntr(USF)=0,0
Exp/Cntr=0.3,0.1

Type RM Length L Ch R = 1 ,2317    ,98.5,115.3,136.6
XS GIS Cut Line= 4
2161499.47162129 485133.726921282161342.75162085485254.175480569
 2161316.0613151485328.0870964962161318.11441554485365.727271274
#Sta/Elev= 30
       0 2767.17     4.2  2766.7    14.2 2762.75    31.9 2760.87    49.6 2754.38
    59.7  2751.7    73.3 2746.31    79.8 2744.52    84.9 2744.21    98.9 2745.54
   105.1 2744.77   110.4 2743.36   120.2 2739.04   140.4 2732.71     156 2730.97
   175.7 2732.45   180.7 2732.23   190.8  2729.9   205.1 2728.94  212.59 2726.95
   222.1 2726.13   231.7 2726.93   239.1 2728.69   243.4 2728.35   251.9 2728.96
   255.1 2730.83   267.6    2743   276.2 2750.48   301.4 2769.39   313.9  2780.4
#Mann= 3 ,-1,0
       0      .1       0  212.59    .045       0   231.7      .1       0
Bank Sta=212.59,231.7
XS Rating Curve= 0 ,0
Exp/Cntr(USF)=0,0
Exp/Cntr=0.3,0.1

Type RM Length L Ch R = 1 ,2201    ,143.6,147.1,152.4
XS GIS Cut Line= 3
2161476.79323054485123.7159639822161291.48534901485203.027737278
2161131.37933936485217.111136275
#Sta/Elev= 30
       0 2763.66     7.7 2761.82    19.9 2757.69    35.1 2749.66    41.2  2747.2
    70.3 2741.38    83.3 2740.31   100.7 2734.76   108.2 2732.91   135.6  2730.3
   147.8    2727     153 2726.28     166 2725.93   175.3 2726.95   187.8 2725.89
   201.6 2726.61   212.9 2726.06     225 2724.08   232.4  2720.5   249.1 2719.58
   257.1 2720.45     262 2721.64   273.2 2721.81   293.2 2730.18     321 2750.96
   337.4 2764.75   341.4 2767.51   345.4 2768.98   349.4 2769.58   362.3 2768.67
#Mann= 3 ,-1,0
       0      .1       0   232.4    .045       0   257.1      .1       0
Bank Sta=232.4,257.1
XS Rating Curve= 0 ,0
Exp/Cntr(USF)=0,0
Exp/Cntr=0.3,0.1

Type RM Length L Ch R = 1 ,2054    ,128,119.5,106.9
XS GIS Cut Line= 4
2161459.82626209485084.0387657962161330.36427299485077.586183038
2161250.39456956485060.2014649022161132.94315906485061.060588486
#Sta/Elev= 30
       0 2767.67     7.7 2764.53    19.7 2760.52    39.7 2750.27    79.8 2734.48
    91.8 2730.95   107.8  2727.1   115.8 2723.12   123.8  2720.6     136 2719.27
   140.1 2718.44   148.2 2717.76     152 2716.04   156.4 2713.27   160.5 2712.46
   164.6 2712.38     181 2712.59     189 2713.26   197.4 2714.92   205.5 2717.42
   209.6 2717.81   233.7 2716.38   245.7 2717.74   253.7  2719.7   265.7 2719.03
   269.7 2719.64   289.3 2726.73   293.7 2727.87   301.7 2728.17   328.9 2725.67
#Mann= 3 ,-1,0
       0      .1       0   156.4    .045       0     189      .1       0
Bank Sta=156.4,189
XS Rating Curve= 0 ,0
Exp/Cntr(USF)=0,0
Exp/Cntr=0.3,0.1

Type RM Length L Ch R = 1 ,1935    ,96.3,83.1,65.4
XS GIS Cut Line= 3
 2161418.0319704484919.5201084542161244.20279961 484966.74141863
2161125.12297395485016.015829248
#Sta/Elev= 30
       0 2804.32    10.2  2797.1    21.6 2787.85    39.2    2771    55.8    2758
    76.5 2736.87    84.4 2729.75    93.1 2720.21      97 2716.94   105.5 2710.32
   109.7 2708.93   116.9 2707.64   122.1 2705.37  124.96 2704.88   139.8 2704.07
   151.1  2704.9   167.7 2707.32     176 2710.05   184.5 2711.83   193.1 2715.64
     197 2714.92   203.4 2712.32   218.8 2711.55   227.9 2715.51   232.1 2716.17
   246.3 2716.85   266.7 2715.04   279.7 2715.53   291.1  2715.1     309 2717.21
#Mann= 3 ,-1,0
       0      .1       0  124.96    .045       0   151.1      .1       0
Bank Sta=124.96,151.1
XS Rating Curve= 0 ,0
Exp/Cntr(USF)=0,0
Exp/Cntr=0.3,0.1

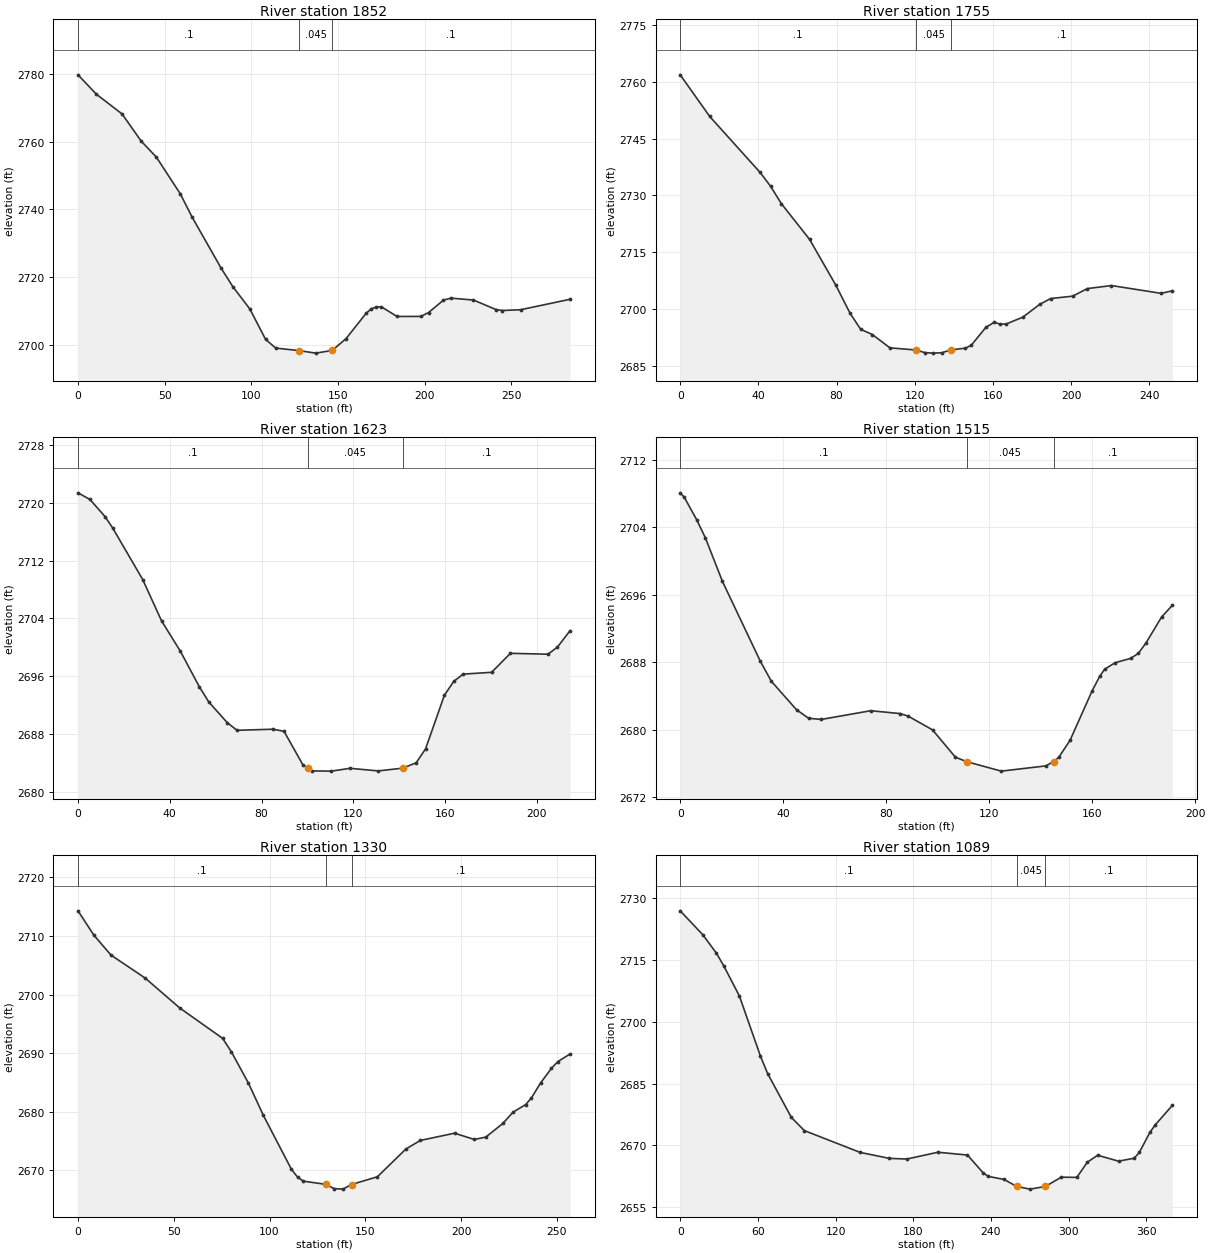
Type RM Length L Ch R = 1 ,1852    ,95.4,97.2,89.5
XS GIS Cut Line= 4
 2161306.4801797484804.5464836782161246.25590005484888.723601817
2161206.56262483484951.6853487182161108.69817041484992.062990753
#Sta/Elev= 30
       0 2779.77    10.6 2774.03    25.4 2768.21    36.5 2760.13    45.2 2755.44
      59 2744.59    65.8 2737.71    82.4 2722.74    89.3 2717.14    99.1 2710.56
   108.2 2701.56     114    2699   127.7 2698.23   137.1  2697.5   146.6 2698.29
   154.6 2701.79   166.2 2709.29   169.1 2710.58     172 2711.13     175 2711.18
     184 2708.34   197.8 2708.35   202.2 2709.51   210.8 2713.17   215.1 2713.76
   228.1 2713.19   241.1 2710.38   244.8  2710.1   255.3 2710.33   283.8 2713.42
#Mann= 3 ,-1,0
       0      .1       0   127.7    .045       0   146.6      .1       0
Bank Sta=127.7,146.6
XS Rating Curve= 0 ,0
Exp/Cntr(USF)=0,0
Exp/Cntr=0.3,0.1

Type RM Length L Ch R = 1 ,1755    ,129.5,131.3,118.2
XS GIS Cut Line= 4
2161249.59931219484769.3943832952161172.74282856484827.246241881
2161141.45033591484890.9902083792161084.30468186484953.219801778
#Sta/Elev= 30
       0 2761.84    15.1 2750.85    40.9 2736.06    46.2 2732.45    51.8  2727.8
    66.2 2718.39    79.5 2706.41    86.9 2698.89    92.3 2694.68    98.3 2693.28
   107.3 2689.77   120.6 2689.21   125.1 2688.52   129.5 2688.38   133.8 2688.48
   138.5 2689.25   145.9 2689.68   148.9 2690.46   156.3 2695.15   160.7 2696.54
   163.8 2695.99   166.8 2696.08   175.3 2697.88   183.8 2701.22   189.5 2702.79
   200.8 2703.42   208.2 2705.41   220.6 2706.22     246 2704.16   251.7 2704.82
#Mann= 3 ,-1,0
       0      .1       0   120.6    .045       0   138.5      .1       0
Bank Sta=120.6,138.5
XS Rating Curve= 0 ,0
Exp/Cntr(USF)=0,0
Exp/Cntr=0.3,0.1

Type RM Length L Ch R = 1 ,1623    ,103.6,107.8,113
XS GIS Cut Line= 2
2161066.95179475484721.7380991672161017.67738413 484930.46997748
#Sta/Elev= 30
       0 2721.42     5.2  2720.5    11.8 2718.12    15.1 2716.55    28.2  2709.4
    36.4 2703.68    44.6 2699.47    52.9 2694.53      57 2692.43      65 2689.58
    69.3  2688.5      85 2688.65    89.8 2688.36    98.1 2683.68  100.06 2683.28
   102.2 2682.87   110.4 2682.84   118.6 2683.23   130.9 2682.87   141.5 2683.25
   147.4 2683.99   151.5 2685.92   159.7 2693.35   163.8 2695.29   167.9 2696.29
   180.3 2696.54   188.5 2699.17   204.9 2699.05     209 2700.04   214.5 2702.31
#Mann= 3 ,-1,0
       0      .1       0  100.06    .045       0   141.5      .1       0
Bank Sta=100.06,141.5
XS Rating Curve= 0 ,0
Exp/Cntr(USF)=0,0
Exp/Cntr=0.3,0.1

Type RM Length L Ch R = 1 ,1515    ,177.6,185.4,186
XS GIS Cut Line= 3
2161001.66382229484707.8850778172160948.29515241484786.455619588
 2160906.1812988484872.903075101
#Sta/Elev= 30
       0 2708.09     1.6 2707.55     6.4  2704.9     9.8 2702.74    16.4 2697.59
    31.1 2688.14    35.4 2685.75    45.2 2682.37    49.9 2681.36    54.8 2681.23
      74 2682.26    85.5 2681.92    88.6 2681.61      98 2679.99   106.9 2676.75
   111.4 2676.21   124.7  2675.1     142 2675.72     145 2676.23     147 2676.72
   151.4 2678.75   159.9 2684.56   162.9 2686.32   164.8 2687.17   168.9 2687.95
   174.9 2688.46   177.9 2689.05   180.9 2690.29     187 2693.39   191.1 2694.74
#Mann= 3 ,-1,0
       0      .1       0   111.4    .045       0     145      .1       0
Bank Sta=111.4,145
XS Rating Curve= 0 ,0
Exp/Cntr(USF)=0,0
Exp/Cntr=0.3,0.1

Type RM Length L Ch R = 1 ,1330    ,249,240.7,231.7
XS GIS Cut Line= 2
2160883.06677811484561.862467167 2160766.6934285484790.903008745
#Sta/Elev= 30
       0  2714.3     8.2 2710.18    17.2 2706.75    35.1 2702.81    53.1 2697.72
    75.5 2692.53      80 2690.27      89 2684.87    96.8 2679.36   111.4 2670.19
   114.7  2668.8   117.7 2668.15   129.3 2667.61   133.8 2666.87   138.3 2666.79
   142.8 2667.58   156.3  2668.9   171.2 2673.64   178.7  2675.1   196.6 2676.34
   206.9 2675.27   212.9 2675.67   221.8    2678   227.1 2679.92   233.7 2681.22
   236.7 2682.35   241.5 2684.91   247.2 2687.42   250.5 2688.56   256.9 2689.86
#Mann= 3 ,-1,0
       0      .1       0   129.3    .045       0   142.8      .1       0
Bank Sta=129.3,142.8
XS Rating Curve= 0 ,0
Exp/Cntr(USF)=0,0
Exp/Cntr=0.3,0.1

Type RM Length L Ch R = 1 ,1089    ,214.6,223,228.3
XS GIS Cut Line= 3
2160740.00909356484408.4275412562160592.50401986484555.932614958
2160611.03480801 484726.41586597
#Sta/Elev= 30
       0 2726.98    17.4 2721.19      28 2716.69    33.7 2713.58    45.7 2706.31
      62 2691.68    67.6 2687.41    85.9 2676.78    95.9  2673.6     139  2668.3
   161.6 2666.85   175.1 2666.69   199.1 2668.34   221.9 2667.66     234 2663.35
     238 2662.47   250.1 2661.74     260 2660.03   270.2 2659.38     282 2660.02
   294.4 2662.28   306.4 2662.23   314.5 2665.92   322.5 2667.61   338.6 2666.17
   350.7 2666.89   354.7 2668.29   362.8 2673.15   366.8 2674.93   380.1  2679.7
#Mann= 3 ,-1,0
       0      .1       0     260    .045       0     282      .1       0
Bank Sta=260,282
XS Rating Curve= 0 ,0
Exp/Cntr(USF)=0,0
Exp/Cntr=0.3,0.1

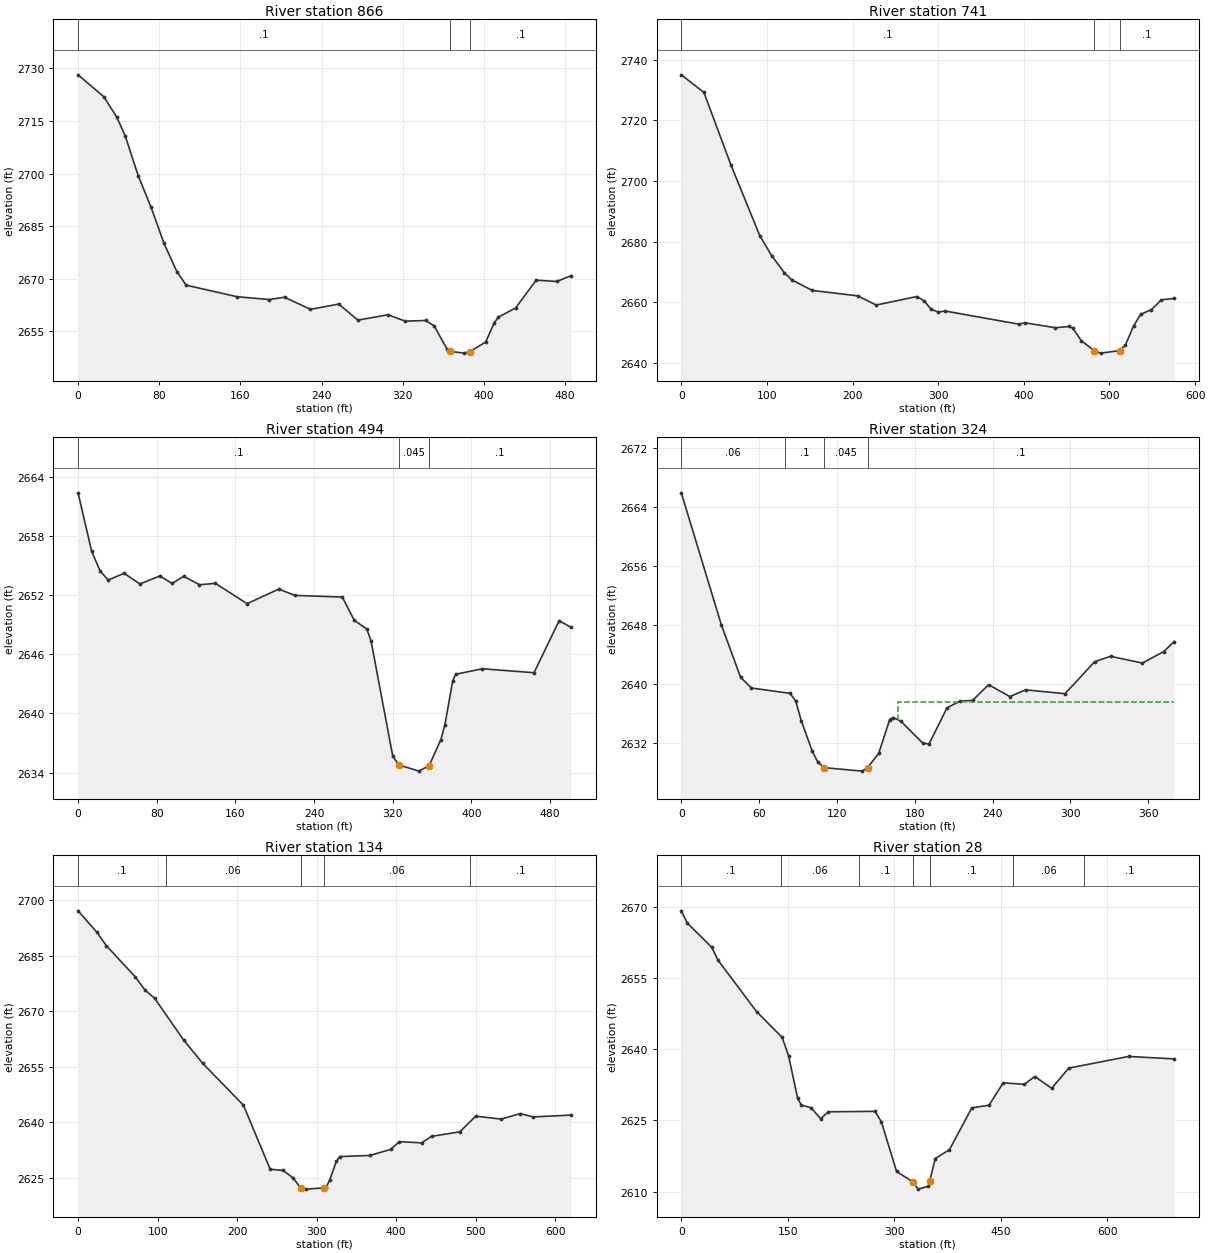
Type RM Length L Ch R = 1 ,866     ,126.3,125.6,126.1
XS GIS Cut Line= 4
2160739.97562608484396.956050627  2160425.486075484508.670249368
2160394.50650728484603.4865020822160386.05753427484655.119114946
#Sta/Elev= 30
       0 2728.17    25.3 2721.94      38  2716.2    46.5 2710.74    59.2 2699.45
      72 2690.36    84.7  2680.1    97.4 2672.05   106.5 2668.19   156.8 2664.89
     188  2664.1   203.5 2664.75     229 2661.29   256.9  2662.8   275.7 2658.22
   305.4 2659.75   322.4 2657.93   342.7 2658.12   351.1 2656.52   363.7 2649.87
  366.79 2649.29   380.6 2648.81   385.9 2649.27   401.6 2651.94     410 2657.39
   414.2 2659.09   431.1 2661.67   451.4 2669.61   471.7 2669.24   485.8  2670.9
#Mann= 3 ,-1,0
       0      .1       0  366.79    .045       0   385.9      .1       0
Bank Sta=366.79,385.9
XS Rating Curve= 0 ,0
Exp/Cntr(USF)=0,0
Exp/Cntr=0.3,0.1

Type RM Length L Ch R = 1 ,741     ,227.8,246.6,267.2
XS GIS Cut Line= 3
2160734.07924135484378.7782802112160305.86848396484465.587090097
2160267.27282254484598.920097194
#Sta/Elev= 30
       0 2735.04    26.4 2729.25    57.9 2705.35    91.7 2681.93   105.5 2675.39
   120.3 2669.75   129.2 2667.35     153  2663.9     206 2662.11   227.6 2659.08
   275.1 2661.89   283.6 2660.44   291.7 2657.68   299.9 2656.77     308 2657.11
   393.8 2652.78   401.9  2653.2   436.9 2651.58   453.2 2652.03   457.4 2651.38
     467 2647.34   482.3 2643.99   489.6 2643.21   512.2 2644.05   518.7 2645.97
   528.1 2652.14   536.4    2656   548.9 2657.58   560.7  2660.8   575.7 2661.28
#Mann= 3 ,-1,0
       0      .1       0   482.3    .045       0   512.2      .1       0
Bank Sta=482.3,512.2
XS Rating Curve= 0 ,0
Exp/Cntr(USF)=0,0
Exp/Cntr=0.3,0.1

Type RM Length L Ch R = 1 ,494     ,167.9,170.6,171.9
XS GIS Cut Line= 3
2160470.60123647484280.0458854682160186.30914353484317.997295067
2159992.10648369484409.168772782
#Sta/Elev= 30
       0 2662.36    13.8 2656.44    22.6  2654.4    30.7 2653.52    46.8  2654.2
      63 2653.12    83.2 2653.93    95.7 2653.17   107.4  2653.9   123.5 2653.04
   139.7 2653.18   171.9 2651.12   204.2  2652.6   220.4 2651.96   268.8 2651.79
   280.9 2649.43   293.6 2648.56     298 2647.34   320.1 2635.63   326.3 2634.77
   346.6 2634.14     357 2634.69     369 2637.34   373.1 2638.84     381 2643.28
     384 2643.96   411.1 2644.52   463.7 2644.12   489.3 2649.39   501.4 2648.72
#Mann= 3 ,-1,0
       0      .1       0   326.3    .045       0     357      .1       0
Bank Sta=326.3,357
XS Rating Curve= 0 ,0
Exp/Cntr(USF)=0,0
Exp/Cntr=0.3,0.1

Type RM Length L Ch R = 1 ,324     ,209.3,189.8,168.9
XS GIS Cut Line= 3
2160187.03728105484142.5480854242160007.73129819484208.262319978
2159968.30275746484393.200951509
#Sta/Elev= 30
       0 2665.91    30.9 2648.02    45.7 2640.93    54.1 2639.47      84 2638.74
    88.3 2637.67    92.5 2635.03     101 2630.91   105.3 2629.42   110.3 2628.68
   139.4 2628.21   143.6 2628.68   152.2 2630.61   160.7  2635.2   163.3 2635.47
   169.2 2634.99   186.2    2632     191 2631.88   204.9  2636.8     215 2637.69
   224.6 2637.79   236.9 2639.92   253.3 2638.31   265.5 2639.22   295.9  2638.7
   318.7 2643.04     331 2643.76   355.5 2642.85   371.9  2644.4   380.1 2645.77
#Mann= 4 ,-1,0
       0     .06       0      80      .1       0   110.3    .045       0
   143.6      .1       0
#XS Ineff= 2 , 0
                          166.99         2637.63
Permanent Ineff=
       F       F
Bank Sta=110.3,143.6
XS Rating Curve= 0 ,0
Exp/Cntr(USF)=0,0
Exp/Cntr=0.3,0.1

Type RM Length L Ch R = 1 ,134     ,105.7,105.7,105.7
XS GIS Cut Line= 4
2160191.56080448484006.3963728872159936.06023314484041.270637876
2159895.19556364484170.1809743282159901.47513612484397.015594763
#Sta/Elev= 30
       0 2697.17    23.2  2691.5    35.7 2687.72      72 2679.29    84.2 2675.74
    96.3 2673.51   132.6 2662.27   156.8  2655.9     208 2644.57   241.6 2627.27
   257.9 2626.92   270.4  2624.9     280  2622.2   286.4 2621.88   308.7 2622.21
   312.3  2622.5   316.5 2624.37   324.9 2629.44   329.1 2630.69   366.9 2630.99
   393.1 2632.62   404.1 2634.72     432  2634.4   444.6 2636.16   480.1 2637.39
   500.1 2641.61   532.2 2640.83   556.2 2642.32   572.1 2641.41     620 2641.91
#Mann= 5 ,-1,0
       0      .1       0     110     .06       0     280    .045       0
   308.7     .06       0   493.1      .1       0
Bank Sta=280,308.7
XS Rating Curve= 0 ,0
Exp/Cntr(USF)=0,0
Exp/Cntr=0.3,0.1

Type RM Length L Ch R = 1 ,28      ,,,
XS GIS Cut Line= 4
2160106.15141053 483877.265503452159852.97356415484009.446708386
2159801.11786067484085.7050958492159829.61953814484401.188099242
#Sta/Elev= 30
       0  2669.2     8.5 2666.61    42.9 2661.51    51.8 2658.78     106 2647.96
   142.1 2642.51   151.1 2638.65     164 2629.63   169.2 2628.22   182.7 2627.69
   196.3 2625.36   207.2 2626.82     273 2626.91     282 2624.67   303.3 2614.23
   326.3 2612.04   333.7 2610.51   348.2 2611.11  349.86 2612.13   357.8 2616.96
   377.8 2618.83   409.4 2627.66   433.5  2628.2   453.6 2632.93   483.3 2632.61
     498 2634.26   521.9 2631.78   545.9 2636.03   630.3 2638.49   694.6 2637.97
#Mann= 7 ,-1,0
       0      .1       0     140     .06       0     250      .1       0
   326.3    .045       0  349.86      .1       0  467.83     .06       0
  567.83      .1       0
Bank Sta=326.3,349.86
XS Rating Curve= 0 ,0
Exp/Cntr(USF)=0,0
Exp/Cntr=0.3,0.1
LCMann Table=0

Chan Stop Cuts=-1
Use User Specified Reach Order=0
Composite Channel Slope=5